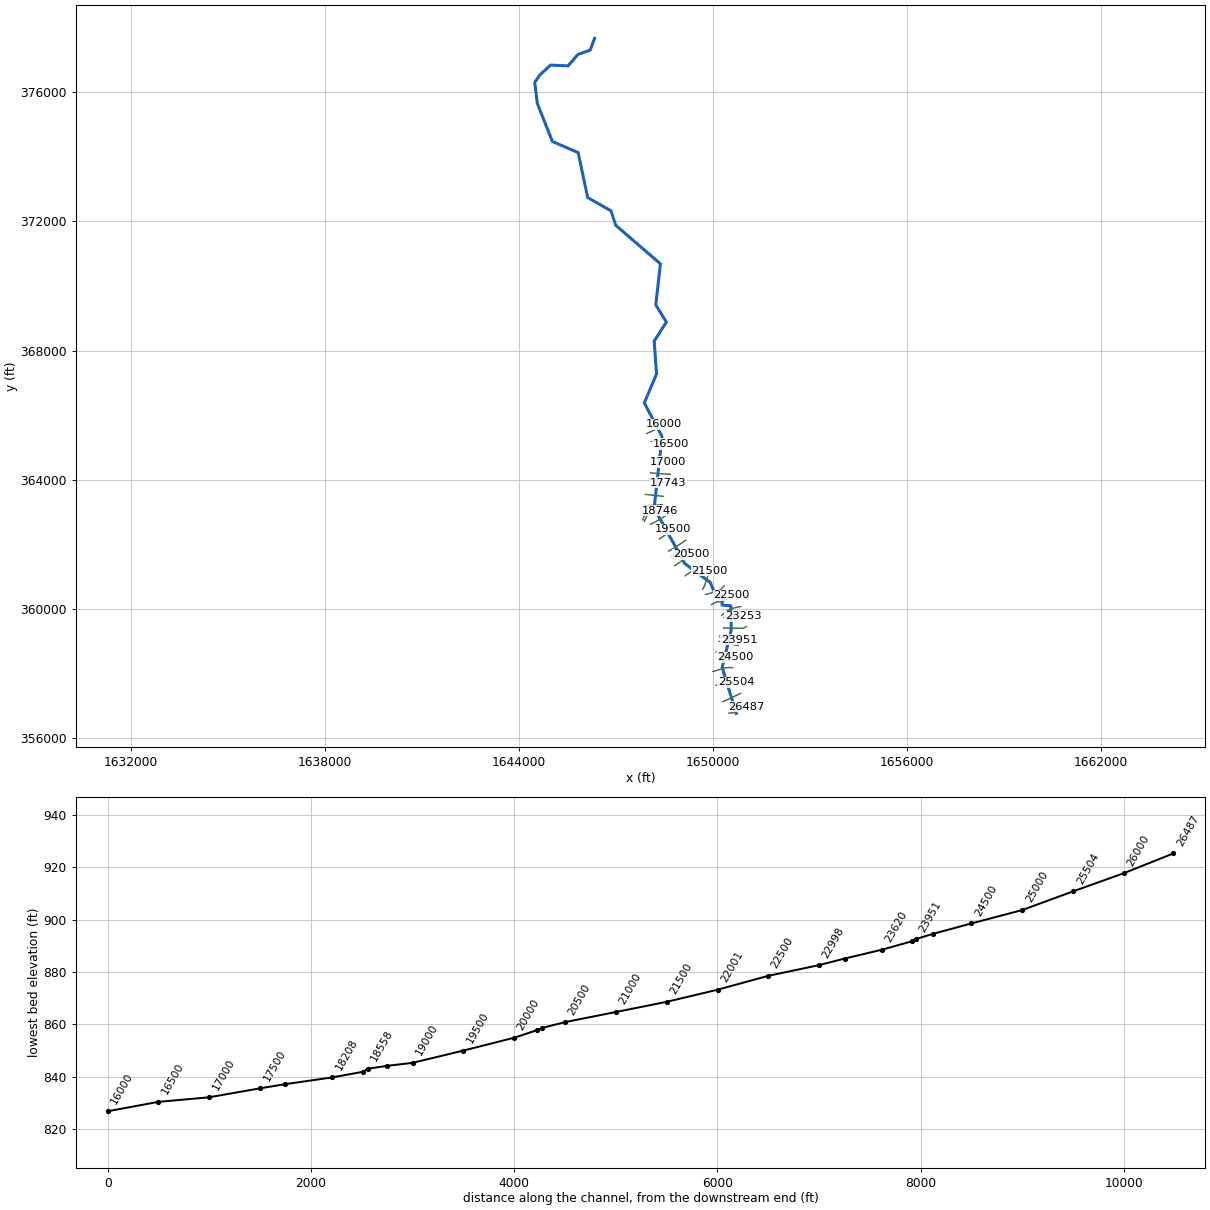
--- BUFFALORN.prj (project) ---

Proj Title=BUFFALORN
Current Plan=p01
Default Exp/Contr=0,0
English Units
Geom File=g01
Flow File=f01
Plan File=p01
BEGIN DESCRIPTION:
---------- MODELED AS PART OF WVEMD CTP PROGRAM, 2023----------
Stream Name: Buffalo Run
Flood Zone:  AFH
Wetzel County, WV
HEC-RAS Version: RAS 6.3
Vertical Datum: NAVD88
Projection: NAD 1983 StatePlane West Virginia S FIPS 4702 (US Feet)
Terrain: 1-meter West Virginia FEMA R3 South Central (collected 2018-2020)
Land Use: 2019 NLCD
Hydrologic Method:
WV 2010 Regional Regression Equations
Additional Model Notes:
None
END DESCRIPTION:
DSS Export Rating Curves= 0
DSS Export Rating Curve Sorted= 0
DSS Export Volume Flow Curves= 0
DXF OffsetX= 0
DXF OffsetY= 0
DXF ScaleX= 0
DXF ScaleY= 0

--- BUFFALORN.p01 (plan) ---

Plan Title=Floodplain
Program Version=4.00
Geom File=g01
Flow File=f01
K Sum by GR=0
Std Step Tol=0.01
Critical Tol=0.01
Num of Std Step Trials=20
Max Error Tol=0.3
Flow Tol Ratio=0.001
Split Flow NTrial=30
Split Flow Tol=0.02
Split Flow Ratio=0.02
Log Output Level=0
Friction Slope Method=1
Unsteady Friction Slope Method=2
Unsteady Bridges Friction Slope Method=1
Global Log Level=0
CheckData=False
Run HTab=0
Run UNet=0
Run PostProcess=0
UNET Theta=0
UNET Theta Warmup=0
UNET ZTol=0
UNET ZSATol=0
UNET MxIter=0
UNET MaxInSteps=0
UNET DtIC=0
UNET DtMin=0
UNET MaxCRTS=0
UNET WFStab=0
UNET SFStab=0
UNET WFX=0
UNET SFX=0
UNET DSS MLevel=0
UNET DZMax Abort=0
UNET Convert EG Bridges=0
UNET Use Existing IB Tables=0
UNET Froude Limit=0
UNET Froude Power=0
Write IC File=0
Echo Input=False
Echo Output=False
Write Detailed=0

--- BUFFALORN.f01 (steady flow) ---

Flow Title=Flow
Program Version=6.31
Number of Profiles= 1
Profile Names=F01pct
River Rch & RM=BUFFALORN,Main            ,26487
     786
River Rch & RM=BUFFALORN,Main            ,25000
     921
River Rch & RM=BUFFALORN,Main            ,23620
    1040
River Rch & RM=BUFFALORN,Main            ,23253
    1260
River Rch & RM=BUFFALORN,Main            ,19000
    1640
River Rch & RM=BUFFALORN,Main            ,18208
    1860
River Rch & RM=BUFFALORN,Main            ,14001
    2280
River Rch & RM=BUFFALORN,Main            ,6500
    2540
Boundary for River Rch & Prof#=BUFFALORN,Main            , 1
Up Type= 0
Dn Type= 3
Dn Slope=0.0084
DSS Import GetInterval= 0
DSS Import GetPeak= 0
DSS Import FillOption= 0

--- BUFFALORN.g01 (geometry) ---

Geom Title=Geometry
Program Version=6.31

River Reach=BUFFALORN       ,Main
Reach XY= 30
     1650728.918      356773.656     1650292.139      358191.622
     1650572.044       359351.72     1650563.046      360102.969
     1650289.831      360122.299     1650284.927        360405.9
     1650088.743      360435.039     1649923.808       360825.35
     1649134.025      361410.475     1648188.072       363124.94
     1648433.499      365337.752     1647884.437      366378.625
      1648262.65      367277.949     1648190.073      368293.578
     1648568.285      368881.858     1648239.659      369411.986
     1648382.109      370684.114     1647001.228      371875.888
     1646854.017      372323.156     1646134.163      372733.797
     1645839.037      374124.905     1645043.563       374468.04
     1644576.094      375647.756     1644495.403      376297.343
     1644651.376      376524.992     1644983.608       376832.43
     1645526.809      376808.088     1645832.444      377161.957
     1646210.205      377296.292       1646348.6      377660.622

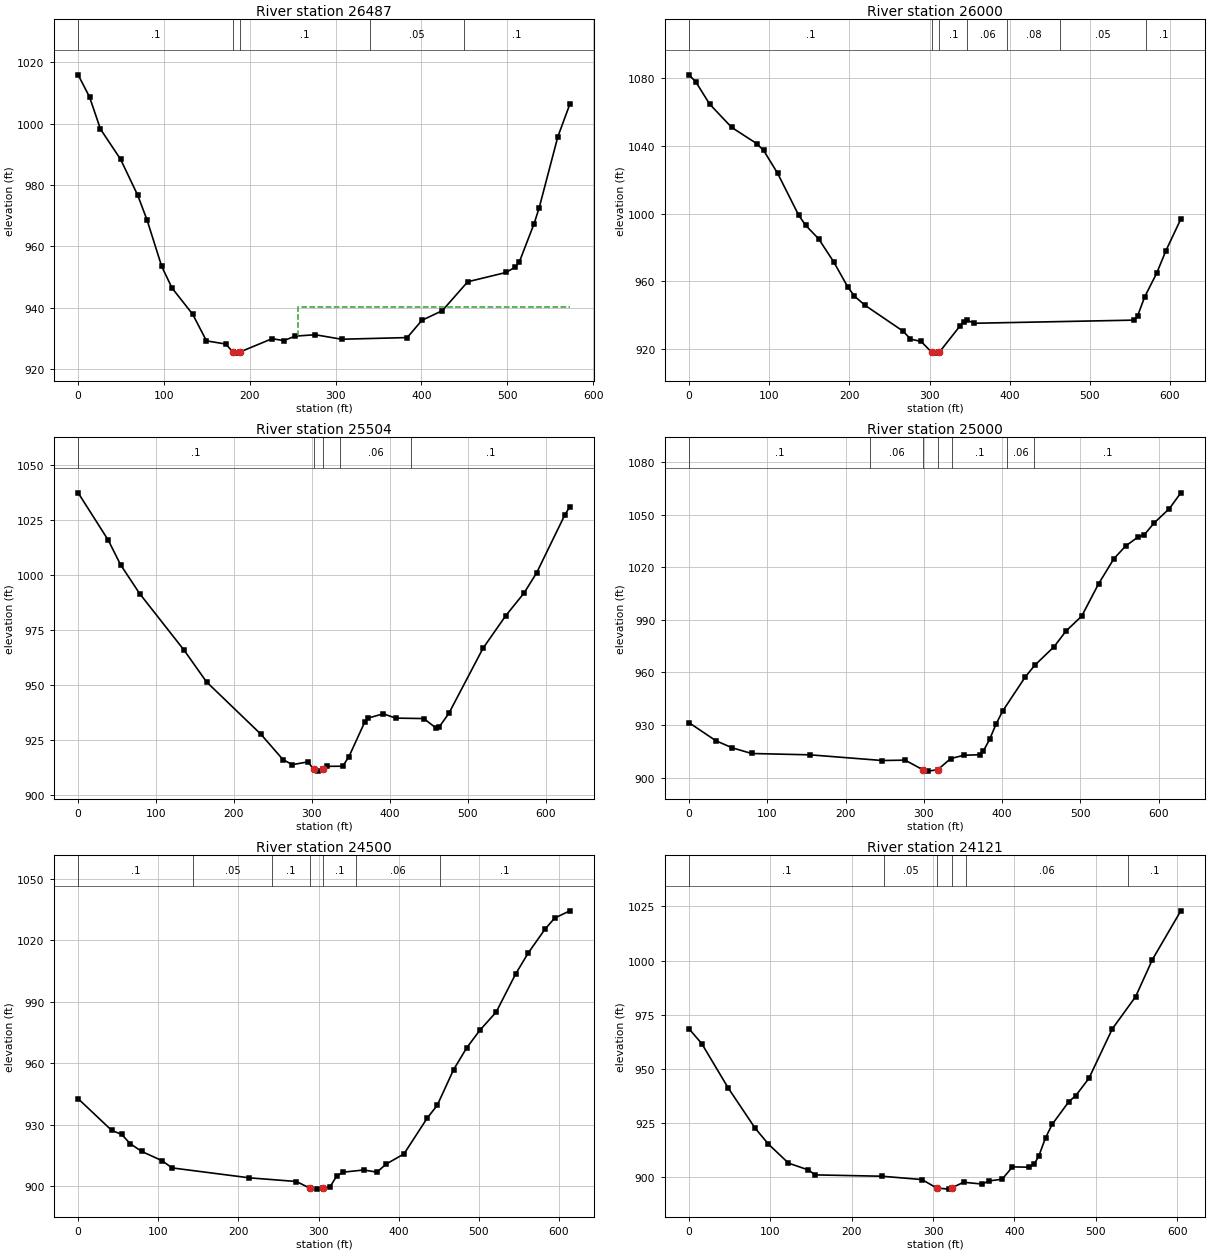
Type RM Length L Ch R = 1 ,26487   ,487.2,487.4,487.4
XS GIS Cut Line= 3
1650502.77973032356784.0486825951650652.21464842356790.458979094
1651028.49567105356984.321123561
#Sta/Elev= 30
       0 1015.84    13.3 1008.63      26  998.19    49.4  988.39    69.4  976.67
    80.4  968.53    97.4  953.48   109.4  946.47   133.5  937.93   149.5  929.28
     172  928.25   180.3  925.66   185.5  925.29  188.55  925.66     226  929.99
   239.5  929.36     253  930.83   276.4  931.27   306.9  929.81   383.4  930.35
   400.5  935.96   424.3  939.11   453.9  948.51   498.5  951.53   509.4   953.3
   513.9  954.87   531.2  967.41   537.1  972.53   558.9  995.72   572.9 1006.31
#Mann= 5 ,-1,0
       0      .1       0   180.3    .045       0  188.55      .1       0
  339.57     .05       0  449.57      .1       0
#XS Ineff= 2 , 0
                          255.73          940.22
Permanent Ineff=
       F       F
Bank Sta=180.3,188.55
XS Rating Curve= 0 ,0
Exp/Cntr(USF)=0,0
Exp/Cntr=0.3,0.1

Type RM Length L Ch R = 1 ,26000   ,497,496.1,493.4
XS GIS Cut Line= 6
 1650308.3173615357134.0212664161650393.34311008   357175.035292
1650473.97877559357209.7202620061650542.99143285357239.228733167
1650780.16057792357351.732773259 1650864.8634925357391.912811011
#Sta/Elev= 30
       0 1081.71     8.7 1077.32    25.7 1064.43    53.1 1050.76    84.2 1041.24
      93 1037.17   110.5 1023.65   136.6  999.12   145.3   993.1   161.6   985.1
   180.2  971.68   198.1  956.64   206.3  951.31   219.3  945.99   267.3  930.58
   276.2  926.02   289.5  924.61   302.8   918.2   307.1  917.75  312.07   918.2
   338.2  933.88   342.6  936.25     347   937.1   355.9  935.34   555.1  937.19
   559.5  939.63   568.4  950.89   583.4  964.88   594.9  978.11613.4865  996.75
#Mann= 7 ,-1,0
       0      .1       0   302.8    .045       0  312.07      .1       0
  347.24     .06       0  397.24     .08       0  462.24     .05       0
  569.74      .1       0
Bank Sta=302.8,312.07
XS Rating Curve= 0 ,0
Exp/Cntr(USF)=0,0
Exp/Cntr=0.3,0.1

Type RM Length L Ch R = 1 ,25504   ,501.8,503.5,502.7
XS GIS Cut Line= 6
1650102.95753601357643.7305488441650353.51969892357697.421058252
1650453.63104726 357710.753708751650533.17321101357711.202526748
1650626.78686893357717.3294830021650726.47006851357730.917382345
#Sta/Elev= 30
       0 1037.43    38.7 1015.88    54.4 1004.77    78.9  991.62   136.2  965.77
   164.8  951.44   234.4  927.71   262.9  916.11     275  913.79   295.2  915.08
   302.2   911.6   307.3  910.85  313.97   911.6   319.4  913.03   339.6  913.08
   347.6  917.42   367.7  933.02   371.7  934.91   391.7  936.93   407.7  934.96
   443.7  934.76   459.6   930.4   463.8  931.11   475.8  937.08   519.8  966.78
   548.8   981.5   572.3  991.81   588.5 1001.01   624.8 1027.42631.2076 1031.14
#Mann= 5 ,-1,0
       0      .1       0   302.2    .045       0  313.97      .1       0
  336.25     .06       0  427.25      .1       0
Bank Sta=302.2,313.97
XS Rating Curve= 0 ,0
Exp/Cntr(USF)=0,0
Exp/Cntr=0.3,0.1

Type RM Length L Ch R = 1 ,25000   ,498.6,500.4,490.5
XS GIS Cut Line= 6
1650007.42557484358068.7487276791650253.00185534358141.659014925
1650349.11583634358169.3272666781650421.65998259358188.742910251
1650516.07744467358190.171713173  1650618.700599 358186.66515851
#Sta/Elev= 30
       0  931.28    34.1  921.06    55.1  916.97      80  913.74   154.8  912.97
   246.9  909.73   276.1  909.94  298.69  904.48   305.2  903.68   317.7  904.48
   334.3  910.82     351  912.74   371.7  913.04   375.9     915   384.1  921.85
   392.4  930.64   400.7  937.94   429.7  957.45   441.7  964.05   466.5  974.69
   481.7   983.6   501.7  992.08   523.3 1010.54   542.8 1024.81   557.8 1032.07
   573.8 1037.25   581.8 1038.55   594.5 1045.35   613.8 1053.44 628.397 1062.43
#Mann= 7 ,-1,0
       0      .1       0  231.19     .06       0  298.69    .045       0
   317.7     .06       0  336.17      .1       0  406.19     .06       0
  441.29      .1       0
Bank Sta=298.69,317.7
XS Rating Curve= 0 ,0
Exp/Cntr(USF)=0,0
Exp/Cntr=0.3,0.1

Type RM Length L Ch R = 1 ,24500   ,378,378.7,379.9
XS GIS Cut Line= 6
1650100.25380126358670.082170665 1650189.7864306358642.279076666
1650440.23409243358563.6519373361650511.79037976358541.185774922
1650597.52806917358522.4322035011650690.93962775358508.285578251
#Sta/Elev= 30
       0  942.66    41.7  927.25    54.3  925.23      65   920.7    79.4  916.92
   104.6  912.44   117.2   908.9   213.6  904.06   272.3  902.27     289  899.03
   297.4  898.55   305.8  899.01   314.2  899.58   322.6  905.01     331  906.83
   356.3  907.89   372.9  906.83   384.2  910.75   406.5  915.71   435.7   933.3
     448  939.42   468.4   956.8   484.8  967.47   501.2  976.04   521.6  984.93
   545.9 1003.53   561.6 1013.76   582.3 1025.24   594.5 1030.74613.4919 1034.28
#Mann= 7 ,-1,0
       0      .1       0  143.75     .05       0  241.25      .1       0
     289    .045       0   305.8      .1       0  346.25     .06       0
  451.25      .1       0
Bank Sta=289,305.8
XS Rating Curve= 0 ,0
Exp/Cntr(USF)=0,0
Exp/Cntr=0.3,0.1

Type RM Length L Ch R = 1 ,24121   ,168.9,170.4,172
XS GIS Cut Line= 2
1650197.00561042359001.9639319331650786.20439107358866.607455295
#Sta/Elev= 30
       0  968.49    15.5  961.74    48.3  941.12    81.2  922.69    97.6  915.32
   122.2  906.58   146.8   903.4     155  901.15   237.1  900.53   286.4  898.99
   304.2  895.12   319.2  894.58  322.64  895.12   337.5  897.75   360.3  896.92
   368.5  898.33   384.9  899.18   397.6  904.85   417.7  904.69   424.3  906.07
     430  909.91   438.2  918.24   446.4  924.48     467  934.99   475.2  937.61
   491.6  945.72   520.3   968.5     549  983.39   569.6 1000.47604.5466 1022.96
#Mann= 6 ,-1,0
       0      .1       0     240     .05       0   304.2    .045       0
  322.64     .05       0     340     .06       0     540      .1       0
Bank Sta=304.2,322.64
XS Rating Curve= 0 ,0
Exp/Cntr(USF)=0,0
Exp/Cntr=0.3,0.1

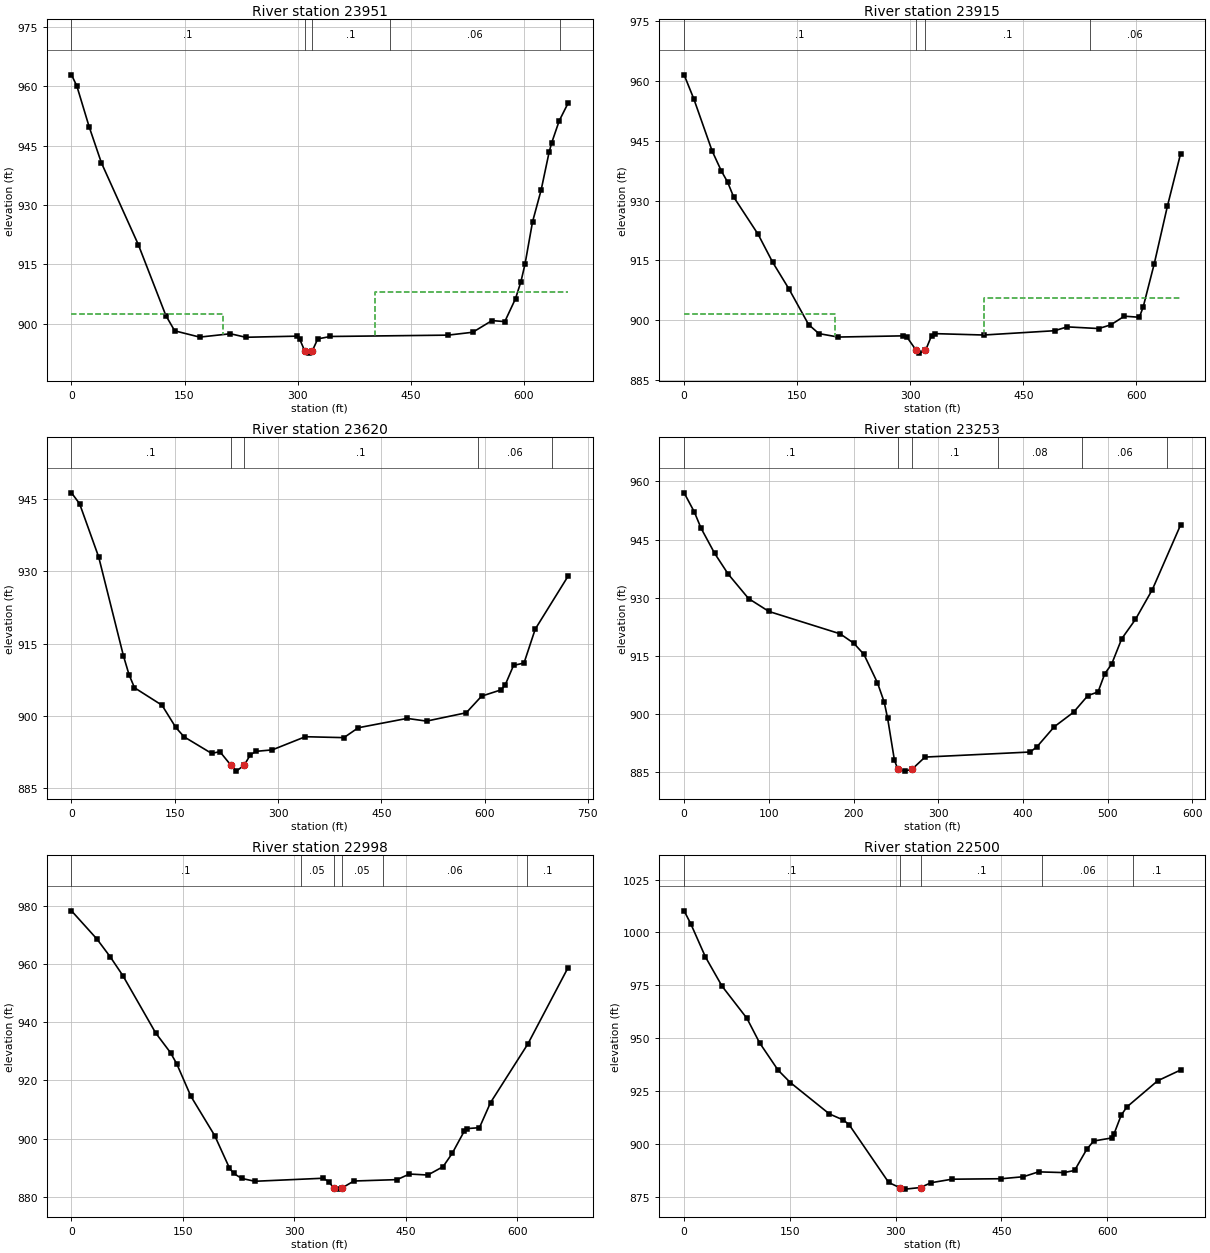
Type RM Length L Ch R = 1 ,23951   ,35.6,35.6,35.5
XS GIS Cut Line= 6
1650225.16232734359134.0268988561650492.79905189359082.192118213
1650510.78254721359099.117760872 1650545.6916852359100.175613538
1650699.08032179359163.6467735091650818.61767307359056.803654224
#Sta/Elev= 30
       0  962.91     7.1  960.08    23.4  949.79    39.7  940.65    88.6     920
   125.2  902.04   136.9  898.18   170.1  896.59   210.8  897.44   231.2  896.55
   298.6  896.83   302.6  896.14  309.31  893.13   314.6  892.54   319.4  893.09
   326.7  896.14   343.5  896.75   499.6  897.09   532.3  897.82   557.8  900.77
   574.8  900.51     589   906.3   596.2  910.62   601.6  915.03   611.6  925.74
     623  933.78   633.7  943.45   637.1  945.77     647  951.29   658.6  955.69
#Mann= 5 ,-1,0
       0      .1       0  309.31    .045       0   319.4      .1       0
  422.23     .06       0  648.23      .1       0
#XS Ineff= 2 , 0
          200.44  902.35  402.42          907.94
Permanent Ineff=
       F       F
Bank Sta=309.31,319.4
XS Rating Curve= 0 ,0
Exp/Cntr(USF)=0,0
Exp/Cntr=0.3,0.1

Type RM Length L Ch R = 1 ,23915   ,293.3,295.4,294.5
XS GIS Cut Line= 6
1650223.57554834359169.4649631731650491.21227289 359117.63018253
1650509.19576821359134.555825189 1650544.1049062359135.613677855
1650697.49354279359199.0848378261650817.03089407359092.241718542
#Sta/Elev= 30
       0  961.51    12.8  955.51    37.2  942.41    49.4  937.41    57.6  934.66
    65.7   930.9    98.3  921.49   117.3  914.58   139.1  907.83   165.1  898.92
   178.7  896.65   204.3  895.78   290.3  896.08   295.8  895.71  308.02  892.41
   312.2  891.75   320.2  892.42   328.2  896.09   332.2  896.64   397.4  896.29
   491.6  897.37   508.1  898.33   550.1  897.91   566.1  898.85     584  901.01
   603.9  900.74     609  903.33   623.7  914.19   641.2  928.66   658.6  941.74
#Mann= 4 ,-1,0
       0      .1       0  308.02    .045       0   320.2      .1       0
  538.23     .06       0
#XS Ineff= 2 , 0
          200.44  901.47   397.8          905.59
Permanent Ineff=
       F       F
Bank Sta=308.02,320.2
XS Rating Curve= 0 ,0
Exp/Cntr(USF)=0,0
Exp/Cntr=0.3,0.1

Type RM Length L Ch R = 1 ,23620   ,366,366.6,366.8
XS GIS Cut Line= 3
1650332.59894696359416.4474409081650940.61028733359406.289733551
1651040.73625985359458.529371387
#Sta/Elev= 30
       0  946.28    11.8  944.01    39.5  932.96    75.5  912.43    83.5  908.58
    91.5  905.83   131.5   902.2   151.5  897.59   163.5  895.65   203.5  892.21
   215.5  892.57   231.5  889.76   239.5  888.53   250.9  889.78   259.6  891.87
   267.6  892.63   291.6  892.94   339.6  895.67   395.6  895.48   416.5  897.53
   487.4  899.47   515.6  898.91   573.3  900.64   595.6  904.09   624.2  905.41
   630.1  906.49     642  910.47   657.2  910.96   673.5     918721.0306  928.95
#Mann= 5 ,-1,0
       0      .1       0   231.5    .045       0   250.9      .1       0
     590     .06       0   698.1      .1       0
Bank Sta=231.5,250.9
XS Rating Curve= 0 ,0
Exp/Cntr(USF)=0,0
Exp/Cntr=0.3,0.1

Type RM Length L Ch R = 1 ,23253   ,253,254.8,256.2
XS GIS Cut Line= 2
1650352.15596729 359748.09270457 1650937.4333912359780.339394592
#Sta/Elev= 30
       0  957.06      12  952.14      20  947.92      36  941.44      52  936.07
    76.1  929.74   100.1  926.41   184.2  920.63   200.3   918.2   212.3  915.32
   228.3  907.96   236.3  902.94   240.3  898.77   248.3  887.99   252.3  885.66
   260.4  885.15  269.13  885.64   284.4  888.78   408.6  890.09   416.6  891.45
     437  896.61   459.8  900.37   476.7  904.67   488.7  905.61   496.7  910.34
   504.7  912.77   516.7  919.37   532.8  924.33   552.8  932.05586.1651  948.76
#Mann= 6 ,-1,0
       0      .1       0   252.3    .045       0  269.13      .1       0
     370     .08       0     470     .06       0     570      .1       0
Bank Sta=252.3,269.13
XS Rating Curve= 0 ,0
Exp/Cntr(USF)=0,0
Exp/Cntr=0.3,0.1

Type RM Length L Ch R = 1 ,22998   ,506.1,498.4,479.6
XS GIS Cut Line= 6
1650280.59005475359809.5552854241650382.62298718359885.110580504
1650458.18057884359958.0041355041650523.59449001359997.932533339
1650693.16436084360045.9439202551650873.16203234360081.049493089
#Sta/Elev= 30
       0  978.31    34.2  968.62    52.1  962.51    69.1  956.05   113.3  936.32
   133.3  929.53   141.8  925.63   160.7  914.55   192.7  901.05   212.6  889.88
   218.1  888.04   229.1   886.3   246.8  885.32   338.4  886.36   346.4  885.24
   352.8  882.98   359.2  882.62  363.86  882.98   380.1  885.41   438.3  885.89
   454.8  887.81   479.6  887.47   500.1  890.33   512.4   894.9   528.7  902.57
   532.8  903.44   549.1  903.75     564  912.36   614.3  932.55 668.253  958.72
#Mann= 6 ,-1,0
       0      .1       0  308.59     .05       0   352.8    .045       0
  363.86     .05       0  418.85     .06       0  613.44      .1       0
Bank Sta=352.8,363.86
XS Rating Curve= 0 ,0
Exp/Cntr(USF)=0,0
Exp/Cntr=0.3,0.1

Type RM Length L Ch R = 1 ,22500   ,491.4,498.5,498.9
XS GIS Cut Line= 6
1649962.21962851360141.1884804221650049.57050367360189.861283332
 1650134.4440216360226.1479561781650309.38002342360232.706670091
1650395.60327618360284.5713957551650581.26202559360430.502206251
#Sta/Elev= 30
       0 1010.22     9.7  1003.9    30.3  988.36    53.8  974.58    89.1  959.35
   107.1  947.75   133.2  934.87   150.6  928.99     206  914.13     226  911.22
   234.1  909.01   290.2  881.69   305.6  879.28   313.7  878.54  335.32   879.3
   350.1  881.56     380  883.24     450  883.46   481.3  884.41   502.7  886.71
   538.8  886.36   553.9  887.38   571.2  897.42   580.9   901.3   606.5  902.75
   609.7  904.56     620  913.54   628.1  917.43   671.7   929.8704.2525   934.9
#Mann= 5 ,-1,0
       0      .1       0   305.6    .045       0  335.32      .1       0
  508.06     .06       0  636.56      .1       0
Bank Sta=305.6,335.32
XS Rating Curve= 0 ,0
Exp/Cntr(USF)=0,0
Exp/Cntr=0.3,0.1

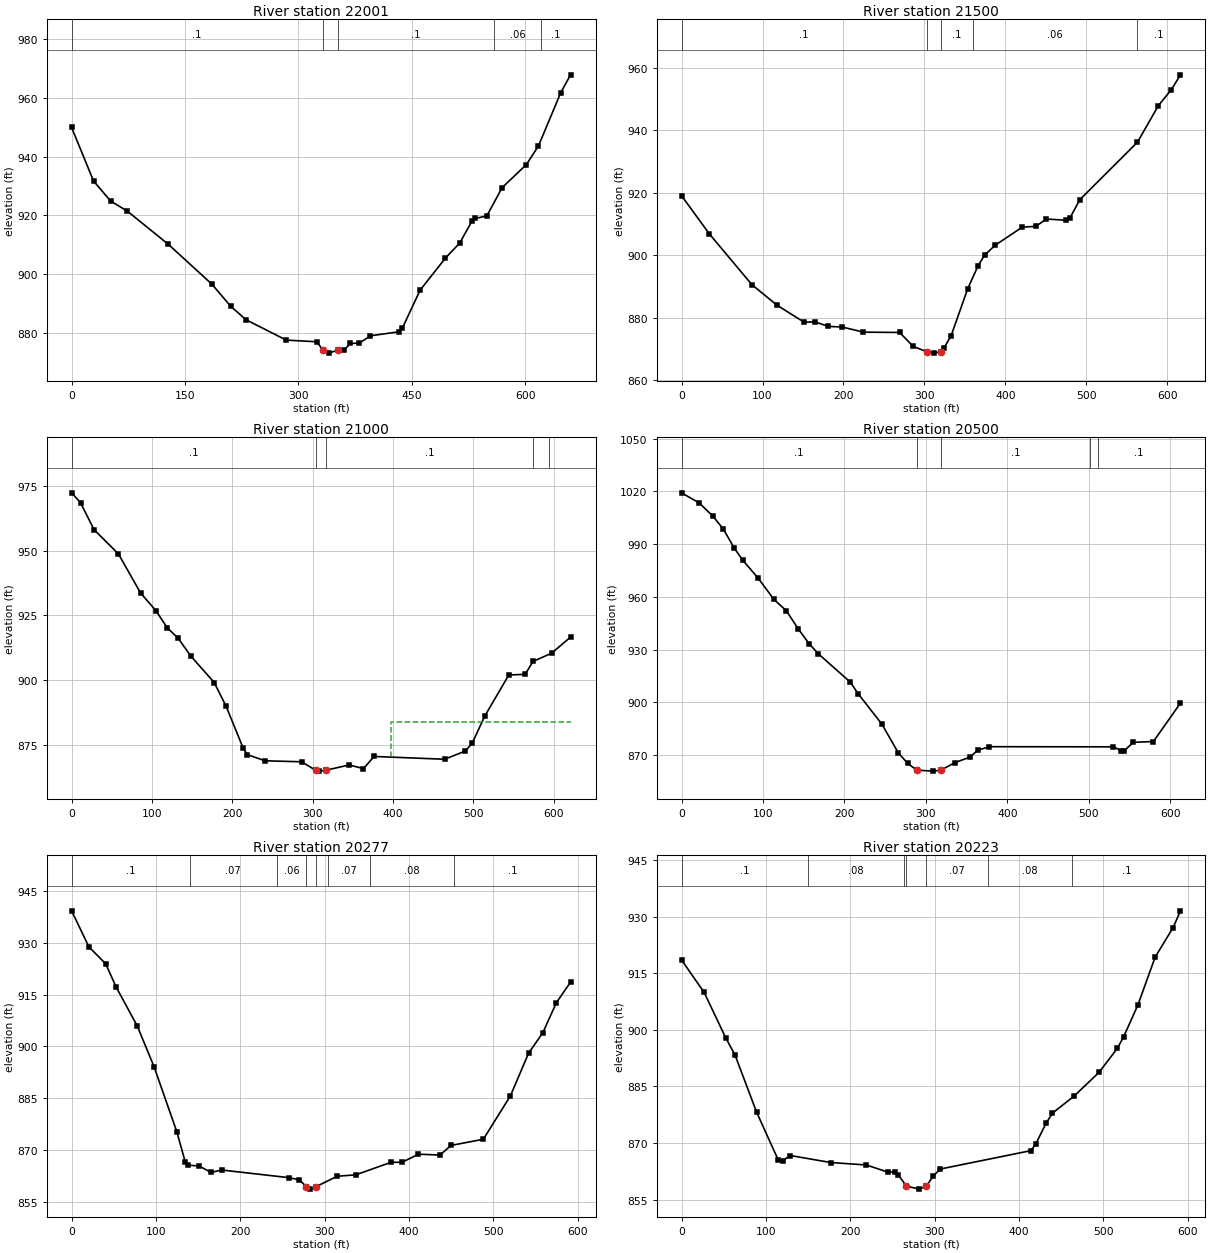
Type RM Length L Ch R = 1 ,22001   ,492.6,501.3,512.7
XS GIS Cut Line= 6
1649777.12091734360451.6225708431649964.70682825360503.126732916
1650048.45502034360521.6404754221650157.00532818360535.860263258
1650221.60526459360580.7794647511650352.60401835360720.483253583
#Sta/Elev= 30
       0  949.88      29  931.71    51.6   924.9    73.9  921.43   127.8  910.23
   185.7  896.63   210.3   889.2   230.8  884.57     284  877.66   324.3   877.1
   332.4  874.34   340.5  873.24   352.6  874.34   360.7  874.32   368.7  876.54
   380.8  876.64   395.4  879.13   432.6  880.47   437.4  881.65     461  894.61
   494.6  905.54   513.5  910.65   529.5  918.01   534.1  918.98   549.3  919.86
   569.6  929.47   601.6  937.27   617.6  943.61   647.2  961.76660.0933  967.77
#Mann= 5 ,-1,0
       0      .1       0   332.4    .045       0   352.6      .1       0
  558.47     .06       0  621.43      .1       0
Bank Sta=332.4,352.6
XS Rating Curve= 0 ,0
Exp/Cntr(USF)=0,0
Exp/Cntr=0.3,0.1

Type RM Length L Ch R = 1 ,21500   ,504.5,500.2,492.1
XS GIS Cut Line= 6
1649687.19065101360614.1547260881649737.34606251360697.214271262
1649767.24856175360779.7583975051649789.18486959360851.493818343
   1649843.32026361017.9101521671649895.16464451361191.563348174
#Sta/Elev= 30
       0  919.01    34.5  906.74    86.9  890.53   117.6  884.01   151.6  878.47
   164.4  878.65   181.4  877.16   198.2  876.98   224.6  875.33   269.3  875.22
   286.2  870.74     303  869.05   311.4  868.61   319.8  869.08     324  870.22
   332.9  874.19   353.4  889.24   366.1  896.55   374.1  899.93   387.1  903.12
   420.8  908.94   437.6  909.19   450.4  911.54   475.1  911.15   479.3  911.74
   491.8  917.73     563  936.14   588.7  947.81   604.8  952.96616.0635   957.7
#Mann= 5 ,-1,0
       0      .1       0     303    .045       0   319.8      .1       0
  359.84     .06       0  562.33      .1       0
Bank Sta=303,319.8
XS Rating Curve= 0 ,0
Exp/Cntr(USF)=0,0
Exp/Cntr=0.3,0.1

Type RM Length L Ch R = 1 ,21000   ,502.1,500,499.7
XS GIS Cut Line= 6
1649151.21304843 361031.908155681649227.99635942361089.019261926
1649304.24489459361132.8715364191649464.06019175361204.174543425
  1649530.478366361240.4139722591649681.12078126361350.853712007
#Sta/Elev= 30
       0  972.46    11.1  968.64    27.9  958.21    58.3   948.8    85.9  933.66
   105.1  926.79   118.9  920.26   132.7  916.15   148.2  909.34   177.5  899.03
   192.3  889.86   213.6   873.6   218.6  871.14   240.8  868.72   286.3  868.34
  303.87  865.05   307.5  864.72   316.6  865.07   345.6  867.11   363.3   865.7
   376.6   870.4   464.3  869.32   490.2   872.5   498.8  875.61   514.4  886.07
   544.3  901.95   564.6  902.18   574.5  907.21   597.6  910.38621.1515   916.6
#Mann= 5 ,-1,0
       0      .1       0  303.87    .045       0   316.6      .1       0
  574.31     .06       0  594.31      .1       0
#XS Ineff= 2 , 0
                           397.8          883.82
Permanent Ineff=
       F       F
Bank Sta=303.87,316.6
XS Rating Curve= 0 ,0
Exp/Cntr(USF)=0,0
Exp/Cntr=0.3,0.1

Type RM Length L Ch R = 1 ,20500   ,226.9,222.6,219
XS GIS Cut Line= 6
1648825.18023592361345.5768196731648903.50389817361397.185968429
 1649036.2611786361490.8967390061649117.95852175361548.564274594
1649179.23136508361591.8151723441649327.30718443361696.338585332
#Sta/Elev= 30
       0 1019.16    21.6 1013.46    38.9  1005.7    51.4  998.46    64.9  987.63
    75.4  980.71    93.8   970.8   113.5   958.5   128.8  952.02   143.5  941.63
   156.9  933.19     168  927.59   207.2  911.48   216.9  904.83   245.9  887.66
     266  871.37   277.5  865.31   288.9  861.41     309  860.86  318.45  861.41
   335.4  865.67     354  868.82   363.8  872.76   377.9  874.76     530  874.68
   540.1  872.51   543.5  872.49   554.8  877.26   579.3  877.69612.5482  899.57
#Mann= 5 ,-1,0
       0      .1       0   288.9    .045       0  318.45      .1       0
   501.3     .06       0   511.3      .1       0
Bank Sta=288.9,318.45
XS Rating Curve= 0 ,0
Exp/Cntr(USF)=0,0
Exp/Cntr=0.3,0.1

Type RM Length L Ch R = 1 ,20277   ,55,54.3,53.9
XS GIS Cut Line= 3
1648766.21215729361564.7873790361648864.56456186361682.487797618
1649283.77153215361809.862223206
#Sta/Elev= 30
       0   939.3    20.5  928.86    40.4  923.94    52.9  917.17    77.8  905.94
    97.7  894.16   124.8  875.23   134.6  866.63   137.5   865.6   150.8  865.38
   165.5  863.51     178   864.2   257.7  861.98     270  861.35   278.3  859.38
   282.5  858.66  289.71  859.37     315   862.4   336.9   862.8   378.7  866.43
   391.9  866.45   411.2  868.78   436.8  868.54   449.7  871.32   488.1  873.11
   520.2  885.68   541.7  898.02   558.7  904.01   574.7  912.69591.5147  918.65
#Mann= 8 ,-1,0
       0      .1       0     140     .07       0  243.38     .06       0
   278.3    .045       0  289.71     .06       0  303.38     .07       0
  353.38     .08       0  453.38      .1       0
Bank Sta=278.3,289.71
XS Rating Curve= 0 ,0
Exp/Cntr(USF)=0,0
Exp/Cntr=0.3,0.1

Type RM Length L Ch R = 1 ,20223   ,221.5,223.1,220.4
XS GIS Cut Line= 3
1648750.89497953361616.382083072 1648849.2473841361734.082501654
1649268.45435439361861.456927242
#Sta/Elev= 30
       0  918.51    26.9  909.88    52.3  897.92    63.5  893.27      89  878.19
   114.9  865.38   120.1   865.3   128.8  866.69   176.9  864.83   219.1  864.18
   244.2  862.32   252.5  862.27   256.7  861.62   266.7  858.58   281.8  857.78
  290.41  858.59   298.5   861.3   306.9  863.11   414.2  867.98   419.8  869.67
   432.3  875.29   439.8  877.92   465.5  882.45     495  888.73   516.8  895.11
   524.3  898.22     541  906.55   561.6   919.3   582.8  927.08591.5147  931.52
#Mann= 7 ,-1,0
       0      .1       0     150     .08       0  263.38     .07       0
   266.7    .045       0  290.41     .07       0  363.38     .08       0
  463.38      .1       0
Bank Sta=266.7,290.41
XS Rating Curve= 0 ,0
Exp/Cntr(USF)=0,0
Exp/Cntr=0.3,0.1

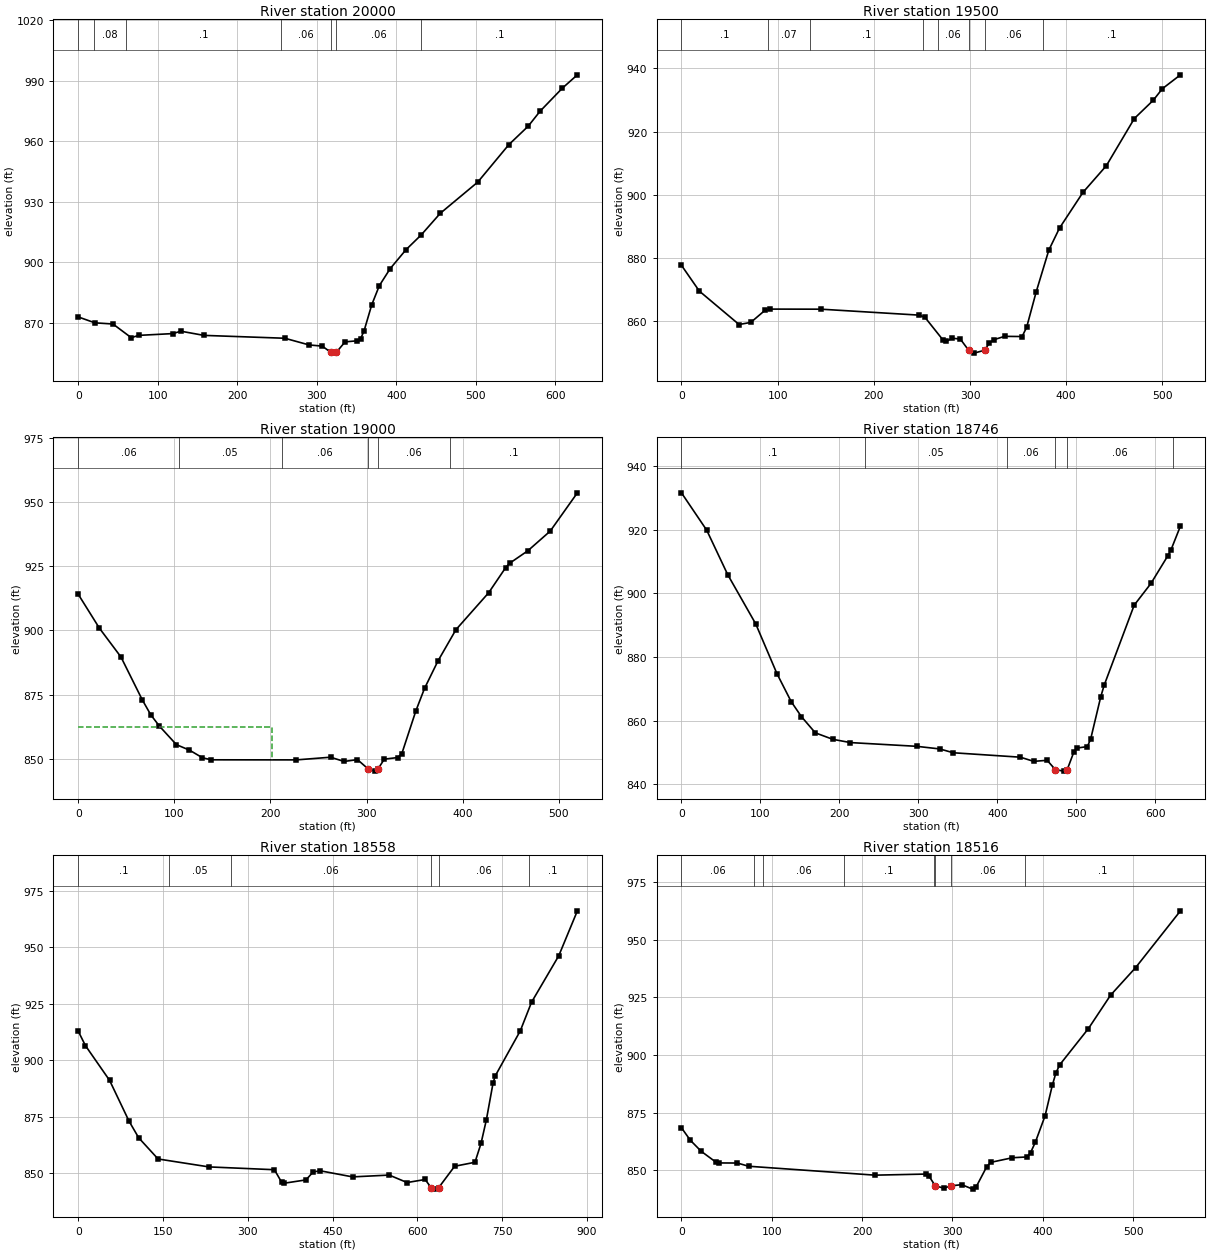
Type RM Length L Ch R = 1 ,20000   ,499.9,500,499.5
XS GIS Cut Line= 6
1648638.37942842361793.8016450111648724.29395476361846.467222095
1648805.38467184 361893.539962591648870.47246817361934.143227845
1649089.84538901 362078.302388341649166.29700775362132.672358334
#Sta/Elev= 30
       0  872.84    20.8  869.93    43.5  869.36    66.5  862.57      76  863.71
   119.1   864.6   128.8  865.79   157.8  863.71   259.7  862.28   290.2  858.96
   306.7  858.38   317.5  855.31   321.1   854.9   324.5  855.34   335.4  860.48
   349.8  860.99     355  862.02   359.4  866.09   368.9  878.82   378.5  888.39
   392.1   896.8     412  906.21   431.2  913.58   455.1  924.27   502.3  939.78
   541.4  958.37   565.7  967.51   580.7  974.97   608.7   986.4627.5627  993.01
#Mann= 7 ,-1,0
       0      .1       0      20     .08       0      60      .1       0
  254.54     .06       0   317.5    .045       0   324.5     .06       0
  431.25      .1       0
Bank Sta=317.5,324.5
XS Rating Curve= 0 ,0
Exp/Cntr(USF)=0,0
Exp/Cntr=0.3,0.1

Type RM Length L Ch R = 1 ,19500   ,500.5,500.2,499.4
XS GIS Cut Line= 6
1648348.78223859362168.5554886761648425.90347542362221.860172093
1648497.88331833362271.6110568341648559.58037342362314.254344255
1648641.84267609362371.1128263321648775.51957409362463.507326588
#Sta/Elev= 30
       0  877.74    18.6  869.59    59.9  859.04    72.1  859.71    86.7  863.49
    91.6  863.91   145.1  863.88   247.2     862   253.2  861.28   271.5   854.3
   275.5   853.7   281.3  854.72   289.9  854.44   298.5  850.93   304.3     850
   315.2  850.93   320.1  853.22     325  854.26   335.9   855.3   354.1  855.24
   358.8  858.11   368.7  869.28   381.9  882.54     393   889.5   417.4  900.78
   441.7   909.2   470.8  924.11   490.3  929.82     500  933.54518.7498  937.91
#Mann= 8 ,-1,0
       0      .1       0      90     .07       0  133.75      .1       0
  251.25     .08       0  266.25     .06       0   298.5    .045       0
   315.2     .06       0  376.25      .1       0
Bank Sta=298.5,315.2
XS Rating Curve= 0 ,0
Exp/Cntr(USF)=0,0
Exp/Cntr=0.3,0.1

Type RM Length L Ch R = 1 ,19000   ,254.7,253.5,252
XS GIS Cut Line= 6
1648076.31427959362623.7435546671648161.10512051362664.987566665
1648238.97602776362705.4999528381648303.35811684362743.990361422
1648389.23392934362795.2307445111648528.44526508362879.012401089
#Sta/Elev= 30
       0     914      22  900.85    44.3  889.73    66.5  873.06    75.4  867.21
    84.3  862.85   102.1   855.6   115.7  853.47   129.2  850.51   138.3  849.71
     227  849.68   262.6  850.72   276.6  849.07   290.6  849.78   301.8  846.14
   309.2  845.31  311.98  846.15   318.5  849.96   332.5   850.6   336.8  852.13
   351.4  868.75   360.4  877.47   374.4  888.15   393.1  900.31   427.2  914.68
   444.9  924.46   449.1  926.17     468  931.01   491.3  938.66519.5584  953.54
#Mann= 6 ,-1,0
       0     .06       0  104.29     .05       0  212.07     .06       0
   301.8    .045       0  311.98     .06       0  387.08      .1       0
#XS Ineff= 2 , 0
          201.54   862.5
Permanent Ineff=
       F       F
Bank Sta=301.8,311.98
XS Rating Curve= 0 ,0
Exp/Cntr(USF)=0,0
Exp/Cntr=0.3,0.1

Type RM Length L Ch R = 1 ,18746   ,189.4,188.3,185.4
XS GIS Cut Line= 3
1647883.69702219362711.6541062011647975.26169756 362902.74560263
1648371.37844537363042.083152109
#Sta/Elev= 30
       0  931.61      32  919.86    58.6  905.88    94.1  890.39   120.9  874.79
   138.9  866.01   151.8   861.3   169.5  856.18   191.7  854.14     214  853.12
   297.6  851.95   326.9  851.13   344.2  849.92   429.1  848.53     446  847.22
     463  847.55  473.48   844.6   484.2  844.15   488.4  844.61   496.9  850.21
   501.1  851.41   513.9  851.86   518.1  854.22   530.8  867.44   535.1  871.08
   573.2   896.3   594.4  903.12   615.5   911.7   619.9  913.74631.8052  921.19
#Mann= 6 ,-1,0
       0      .1       0   231.9     .05       0   411.9     .06       0
  473.48    .045       0   488.4     .06       0   621.9      .1       0
Bank Sta=473.48,488.4
XS Rating Curve= 0 ,0
Exp/Cntr(USF)=0,0
Exp/Cntr=0.3,0.1

Type RM Length L Ch R = 1 ,18558   ,45.1,41.8,43.3
XS GIS Cut Line= 4
1647834.70992086362760.9995040811647986.26936397363151.184453352
1648073.48876004363166.3521677041648449.00936579363189.880481379
#Sta/Elev= 30
       0  912.78    12.4  906.55    55.3  891.14    89.6  873.16   106.8  865.76
   141.1   856.4   231.2  852.89   347.1  851.65     360  846.02   364.3  845.68
   402.9  847.15   415.7  850.68   428.3  851.17   485.4  848.48   550.3  849.28
   581.9  845.98   613.9  847.33  624.33  843.76     630  843.07     638  843.78
   666.1  853.18   702.1  854.94   712.8  863.28   722.2  873.62   734.2   890.1
   738.2  893.24   782.3  913.04   802.3  925.73   850.4  946.22883.3718   966.1
#Mann= 6 ,-1,0
       0      .1       0     160     .05       0     270     .06       0
  624.33    .045       0     638     .06       0  797.11      .1       0
Bank Sta=624.33,638
XS Rating Curve= 0 ,0
Exp/Cntr(USF)=0,0
Exp/Cntr=0.3,0.1

Type RM Length L Ch R = 1 ,18516   ,309.9,308.2,308
XS GIS Cut Line= 2
1647890.32917305363196.6680871611648441.74757243363228.592310284
#Sta/Elev= 30
       0   868.5     9.8   863.1    21.8  858.33    37.8  853.71    41.9  853.27
    61.9  853.23    74.3  851.84   214.1  847.98   270.2  848.45   274.2  847.44
  280.89  843.38   290.3  842.35   298.3  843.36   310.3  843.86   322.3  841.93
   326.3  842.99     338  851.71   342.4  853.53   366.4  855.53   382.4  855.86
   386.4  857.71   391.7  862.23   402.5  873.69   410.5   886.9   414.5  892.29
   418.8  895.82   450.5  911.48     475  925.92   502.6   937.8552.3417  962.44
#Mann= 8 ,-1,0
       0     .06       0      80     .07       0      90     .06       0
     180      .1       0     280     .06       0  280.89    .045       0
   298.3     .06       0     380      .1       0
Bank Sta=280.89,298.3
XS Rating Curve= 0 ,0
Exp/Cntr(USF)=0,0
Exp/Cntr=0.3,0.1

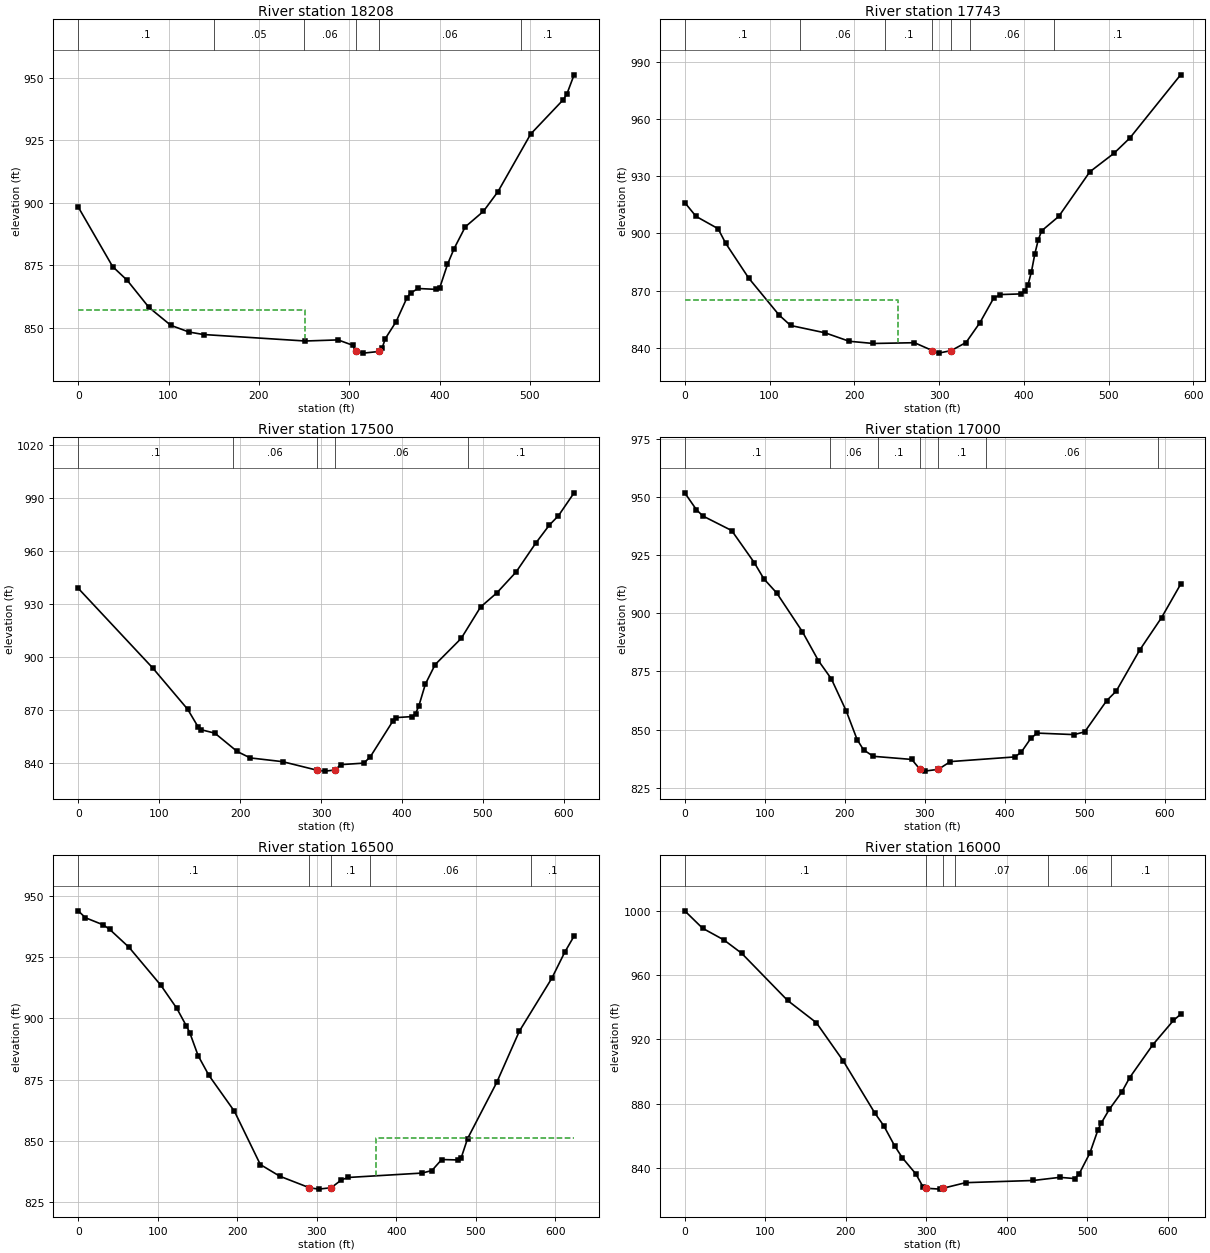
Type RM Length L Ch R = 1 ,18208   ,464.9,464.9,463.4
XS GIS Cut Line= 2
1647922.25339617363549.2856425561648467.86739135363489.790499465
#Sta/Elev= 30
       0  898.33    38.1  874.45    54.2  868.95    78.3  858.07   102.5   850.9
   122.6  848.21   138.7  847.21   251.3  844.61   287.6  845.05   303.7  842.93
   307.7  840.43   315.7  839.75  333.23  840.43   336.2  841.61   339.9  845.56
   351.9  852.39     364  862.05     368  863.85   376.1  865.66   396.2  865.31
   400.2  866.01   408.7   875.3     416  881.62   428.4  890.37   448.5   896.6
   464.6   904.5   500.8  927.58     537  941.39     541  943.76548.8481  951.32
#Mann= 6 ,-1,0
       0      .1       0     150     .05       0     250     .06       0
   307.7    .045       0  333.23     .06       0     490      .1       0
#XS Ineff= 2 , 0
          250.77  857.06
Permanent Ineff=
       F       F
Bank Sta=307.7,333.23
XS Rating Curve= 0 ,0
Exp/Cntr(USF)=0,0
Exp/Cntr=0.3,0.1

Type RM Length L Ch R = 1 ,17743   ,241.7,243.1,243.9
XS GIS Cut Line= 3
1648041.24368235364042.6599998991648152.97846328363984.615957858
1648605.72199119363909.158703206
#Sta/Elev= 30
       0  916.26    13.3     909    39.3  902.53    48.3  894.86    75.4  876.59
   111.4   857.1   124.9  851.67   165.6  847.81     194  843.38   222.4  842.22
     271  842.62   292.1  838.49   299.4  837.15  314.28  838.48   331.8  842.73
   348.1  853.11   364.3  865.97   372.4  867.92   396.7  868.26   400.8  869.69
   404.8  872.89   408.9  879.83     413  889.39     417  896.74   421.1  901.45
   441.1  908.95   477.8   932.4   506.2   942.1     525  950.14584.9003  983.35
#Mann= 7 ,-1,0
       0      .1       0  135.91     .06       0  235.91      .1       0
   292.1    .045       0  314.28      .1       0  335.91     .06       0
  435.91      .1       0
#XS Ineff= 2 , 0
          251.76     865
Permanent Ineff=
       F       F
Bank Sta=292.1,314.28
XS Rating Curve= 0 ,0
Exp/Cntr(USF)=0,0
Exp/Cntr=0.3,0.1

Type RM Length L Ch R = 1 ,17500   ,497.5,500,501.4
XS GIS Cut Line= 6
1648076.67615551364218.1235679981648169.89020792364206.920506418
1648257.11969225364199.9349560891648331.95681292364194.992380679
1648593.88607909364177.6954992561648687.43247992364171.517690092
#Sta/Elev= 30
       0  939.07    92.1  893.94   135.3  870.55   148.3  860.48   152.3  858.97
   168.8  857.09   196.4  846.71   212.5  843.07   252.5  840.95  294.67  836.16
   304.7  835.59   316.7  836.18   324.7  839.27   352.8  840.12   360.8  843.65
   388.8  863.95   392.8  865.89   412.9  866.47   416.8  868.09   420.9  872.57
   428.9  884.84     441   895.9   473.2  910.72   497.1  928.46   517.1  936.43
   540.9  948.23   565.2  964.57   582.2  974.91   593.3  980.12612.6437  993.09
#Mann= 5 ,-1,0
       0      .1       0  191.39     .06       0  294.67    .045       0
   316.7     .06       0  481.39      .1       0
Bank Sta=294.67,316.7
XS Rating Curve= 0 ,0
Exp/Cntr(USF)=0,0
Exp/Cntr=0.3,0.1

Type RM Length L Ch R = 1 ,17000   ,505.2,500,498.4
XS GIS Cut Line= 6
1648085.61642633364655.0229566691648178.97483543364663.633831844
1648266.08785017364671.8821749241648514.80126351364697.212504834
1648535.09637283364698.8595408291648616.75115743364551.680634494
#Sta/Elev= 30
       0  951.74    14.6   944.5    22.6   941.8    58.7  935.53    86.9  921.76
    98.9  914.79     115   908.7     147  892.12   167.2  879.58   183.3   871.8
     202  857.92   215.5  845.72   223.5  841.33   235.6  838.54   283.8  837.19
   294.1  832.93   299.9  832.17     317  832.94   332.1  836.27   412.5  838.27
   420.5  840.22   432.6  846.25   440.6  848.51   486.7  847.86     500  849.04
   527.5  862.47   539.4  866.55   568.6  884.11   596.1  898.14   619.9  912.46
#Mann= 7 ,-1,0
       0      .1       0  181.26     .06       0  241.26      .1       0
   294.1    .045       0     317      .1       0  376.26     .06       0
  591.62      .1       0
Bank Sta=294.1,317
XS Rating Curve= 0 ,0
Exp/Cntr(USF)=0,0
Exp/Cntr=0.3,0.1

Type RM Length L Ch R = 1 ,16500   ,478.4,500,497.9
XS GIS Cut Line= 6
1648100.57276125365189.1331089291648202.80680875365199.306973085
1648292.06680085365191.4946527631648463.97590584 365158.74996759
1648537.65128343365144.716859177  1648715.700468365110.802885011
#Sta/Elev= 30
       0  943.84     9.1  941.02    31.7  938.09    39.7  936.24    63.9  928.97
   104.1  913.42   124.1  904.04     136  896.93   140.2  894.25   150.8  884.81
   164.3  876.81   196.5  862.11     229  840.44   253.5  835.68   290.7  830.99
   302.3  830.42   318.1  830.99   330.8  834.12     339  835.16   432.6  836.97
   444.8     838   457.1  842.48   477.4  842.31   481.5  843.06   489.6  850.98
   526.3   873.9   554.8  894.82   595.5  916.31   611.8  926.96623.5903  933.56
#Mann= 5 ,-1,0
       0      .1       0   290.7    .045       0   318.1      .1       0
  367.34     .06       0  569.84      .1       0
#XS Ineff= 2 , 0
                           373.9           851.4
Permanent Ineff=
       F       F
Bank Sta=290.7,318.1
XS Rating Curve= 0 ,0
Exp/Cntr(USF)=0,0
Exp/Cntr=0.3,0.1

Type RM Length L Ch R = 1 ,16000   ,497,495.3,491.2
XS GIS Cut Line= 6
1647956.09207909365430.5525735911648120.20625217365507.481881678
1648188.11556518365539.3144951761648346.57062884365613.591249511
1648421.66070175 365659.535055251648497.98699267365719.084476843
#Sta/Elev= 30
       0  999.87    22.1  989.07    48.6  981.79    70.7  973.49   127.8  944.14
   163.5  930.33     197   906.5   236.1  874.19   247.4  866.14   260.7  853.81
   270.3  846.36   287.2  836.25     296  828.29   299.3   827.4   317.3  826.84
   321.3  827.43     349  830.86   433.1  832.22   465.9  834.16   484.6  833.41
   489.8  836.11   503.4  849.33   513.5  863.85   517.5  867.92   527.4  876.39
   542.7  886.93   552.8  896.18   581.6  916.64   607.2  931.73616.0887  935.55
#Mann= 6 ,-1,0
       0      .1       0   299.3    .045       0   321.3      .1       0
  336.25     .07       0  451.25     .06       0  529.28      .1       0
Bank Sta=299.3,321.3
XS Rating Curve= 0 ,0
Exp/Cntr(USF)=0,0
Exp/Cntr=0.3,0.1