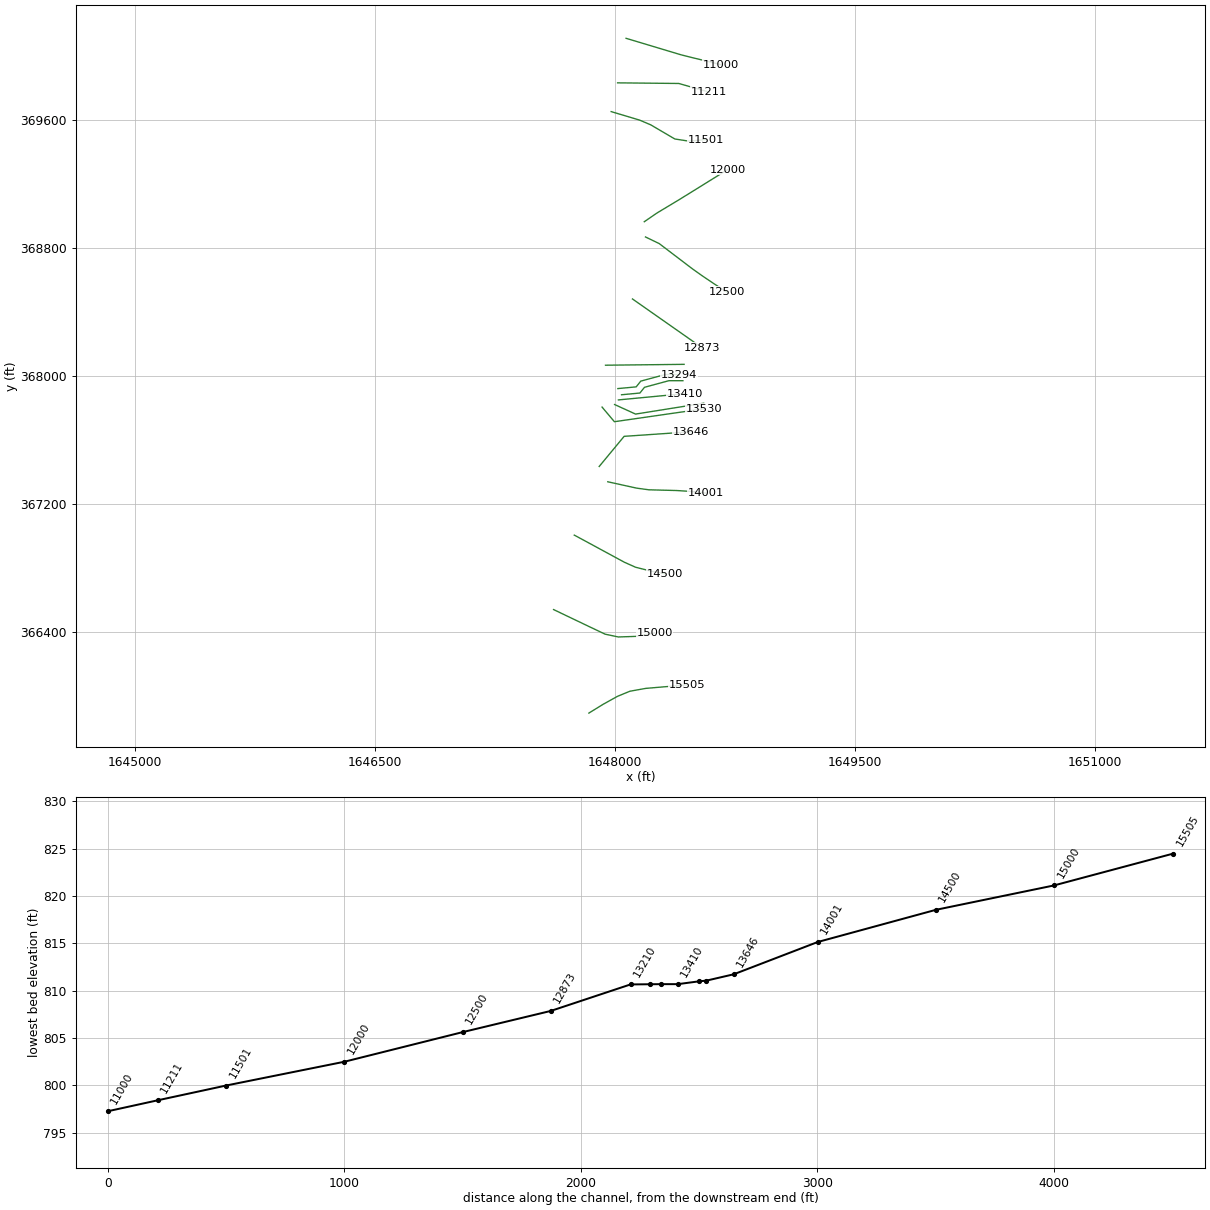
HEC-RAS study BUFFALORN.prj: BUFFALORN

--- BUFFALORN.g01 (geometry) --- (continued)

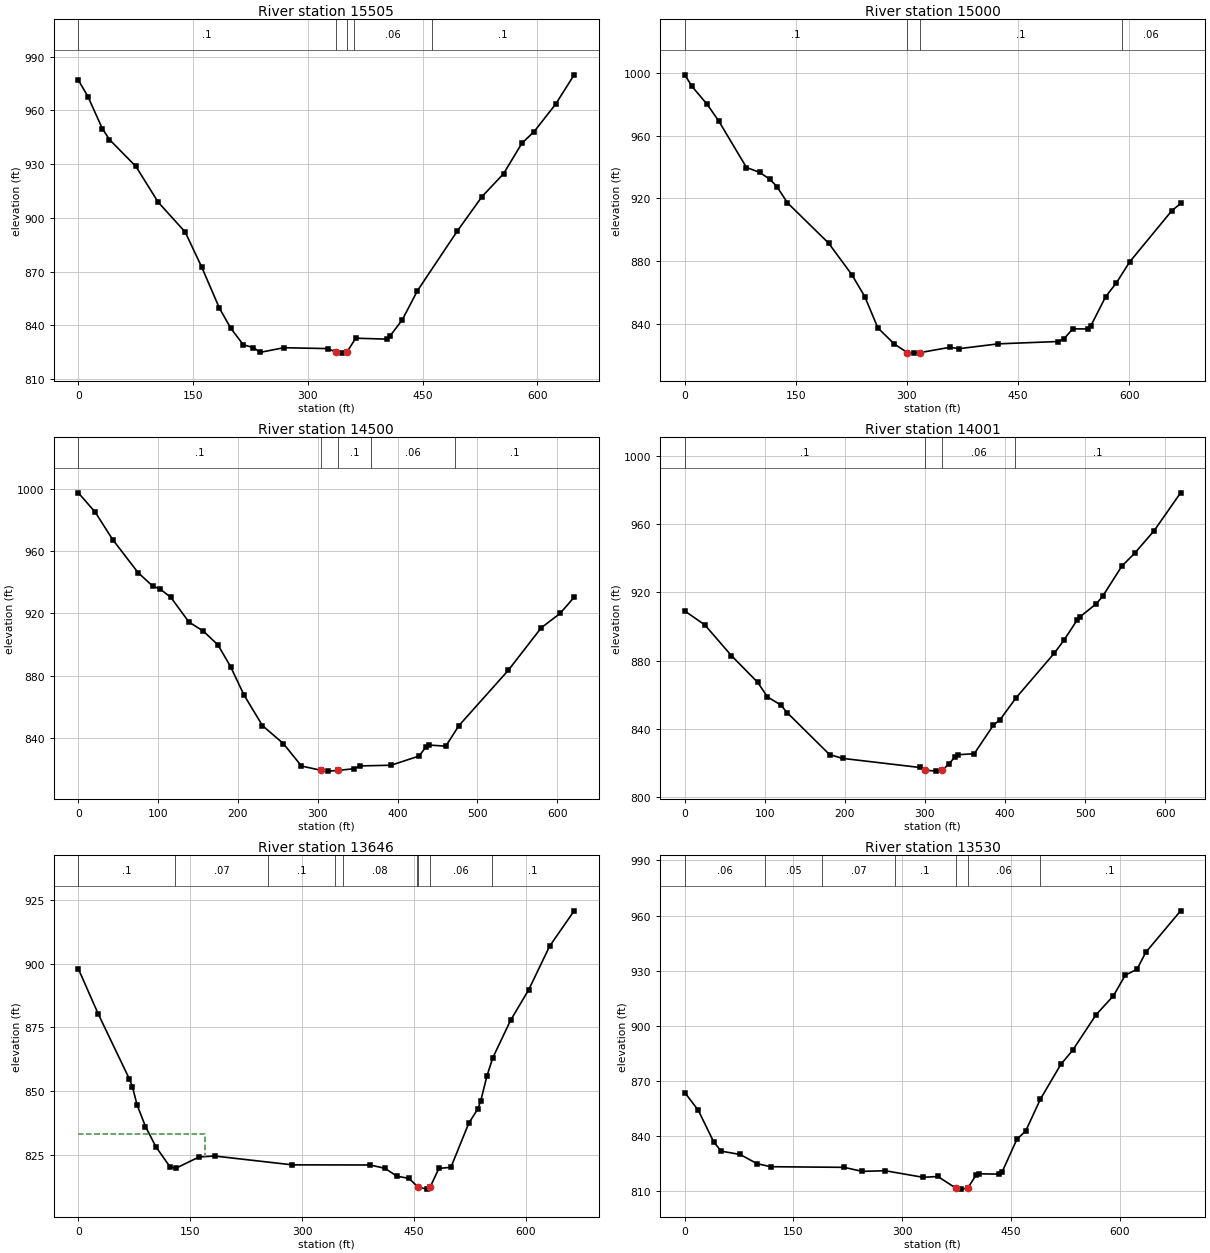
Type RM Length L Ch R = 1 ,15505   ,507.4,504.8,492.2
XS GIS Cut Line= 6
1647837.44336626365895.6494124231647927.34738593365951.050876424
1648015.17365384365999.7991385011648093.41660759366032.088772088
1648192.81109384366049.9338807611648448.13801101366071.663824171
#Sta/Elev= 30
       0  976.93    12.5  967.76    31.3  949.89    40.7  943.72    75.3  928.69
   104.3  908.79   139.6  892.12   161.4  872.38   184.3  849.65   199.3  838.33
   215.7  829.09   228.7  827.63   237.4   824.9   268.6  827.51   325.9  827.02
  336.82  825.05   345.1  824.49  350.94  825.05   362.5  832.83     403   832.3
     407  833.88   423.2     843   443.2  859.37   495.4  892.75   527.5  911.87
   555.6  924.62   579.7  941.71   595.7  948.22   623.8  963.53 647.929  979.87
#Mann= 5 ,-1,0
       0      .1       0  336.82    .045       0  350.94      .1       0
   360.7     .06       0  461.68      .1       0
Bank Sta=336.82,350.94
XS Rating Curve= 0 ,0
Exp/Cntr(USF)=0,0
Exp/Cntr=0.3,0.1

Type RM Length L Ch R = 1 ,15000   ,498.6,499.8,495.7
XS GIS Cut Line= 6
1647616.93691751366542.1848647591647848.10869926366431.624390334
1647939.07898976366388.4515764271648021.34785409366371.059878916
1648130.46410568366374.6671551761648247.77555084366396.235681593
#Sta/Elev= 30
       0  998.96     9.6  991.63    30.1  980.16    45.6  969.63    83.3  939.74
   101.1  936.62   115.1  932.13   124.3  927.57   138.6  917.18   194.2   891.4
   225.6  871.19     243  857.27   260.7  837.23   282.8     827  300.38  821.49
   309.4  821.12   318.2   821.5     358  824.84   370.3  823.97   423.4  827.05
   503.8  828.54   511.8  830.15   523.8  836.66   543.9  836.56   547.9   838.2
   568.2  857.15   582.7  865.98   600.7  879.41   657.6  912.14669.4856  916.74
#Mann= 4 ,-1,0
       0      .1       0  300.38    .045       0   318.2      .1       0
  590.21     .06       0
Bank Sta=300.38,318.2
XS Rating Curve= 0 ,0
Exp/Cntr(USF)=0,0
Exp/Cntr=0.3,0.1

Type RM Length L Ch R = 1 ,14500   ,492.2,499.3,502.3
XS GIS Cut Line= 6
1647746.15745959367007.2472548341647828.66713709366962.757186338
1648059.48097992 366837.73217392  1648128.433926366806.847721249
1648216.87600634366784.375325263 1648313.2764041366765.312699333
#Sta/Elev= 30
       0  997.61    21.2  985.12    43.1  967.48    74.9  946.24    93.1  937.64
   102.2   935.8   115.9  930.36   138.6  914.47   156.8  908.54     175  899.73
   190.8  885.74   207.6  867.52   230.7  847.84   256.9  836.26   279.6  821.84
   304.5  819.01   313.3  818.54  325.41  818.99   345.8  820.12   352.4  821.87
     392  822.35   427.1  828.27   435.6  834.16   439.7  835.32   460.4  834.58
   476.9  847.82   538.6  883.31   580.1  910.78   603.6  919.97621.3134  930.43
#Mann= 5 ,-1,0
       0      .1       0   304.5    .045       0  325.41      .1       0
  366.24     .06       0  471.79      .1       0
Bank Sta=304.5,325.41
XS Rating Curve= 0 ,0
Exp/Cntr(USF)=0,0
Exp/Cntr=0.3,0.1

Type RM Length L Ch R = 1 ,14001   ,353.5,355,354.9
XS GIS Cut Line= 6
1647955.59109583367340.369948179 1648136.0858136367300.573767915
1648212.22640935367290.2322531791648388.41667375367285.624650836
1648475.77050167367279.8677725941648569.08593184367269.837937012
#Sta/Elev= 30
       0  909.14    25.2  900.88    58.1     883      91  867.27   103.3  858.68
   119.6  854.06   127.8   849.5   180.8  824.86     197  822.63   293.6  817.28
  300.05  815.74   313.6  815.14  321.72  815.76   330.1  819.34   337.6  823.72
   341.6  824.77   361.6  825.38   385.6  842.19   393.6   845.2   413.6  858.05
   461.7  884.44   473.7  892.04   489.8  903.61   493.8  905.76   513.8  913.27
   521.8  917.66     546  935.49   562.1  943.11   586.2  956.22619.3546  978.48
#Mann= 4 ,-1,0
       0      .1       0  300.05    .045       0  321.72     .06       0
  412.98      .1       0
Bank Sta=300.05,321.72
XS Rating Curve= 0 ,0
Exp/Cntr(USF)=0,0
Exp/Cntr=0.3,0.1

Type RM Length L Ch R = 1 ,13646   ,115,115.6,116.2
XS GIS Cut Line= 3
1647901.87030322367436.0209922191648057.72930499367624.126684016
1648476.93627528367652.790408481
#Sta/Elev= 30
       0  897.99    26.6  880.33    68.2  854.97    72.5  851.86    78.6  844.78
      90  836.24   103.8  828.38   122.6  820.55   130.5  819.88   161.7  824.31
   182.5  824.69   286.8  821.23     391  821.18   411.1  819.86     427  816.76
   443.1  815.96   455.2  812.52   467.2  811.73  471.48  812.52   483.2  819.84
   499.3  820.27   523.3  837.56   535.3  843.11   539.4   846.4   547.4  855.84
   555.4  863.12   579.5  877.93   603.5  889.72   631.6  906.83 664.472  920.66
#Mann= 9 ,-1,0
       0      .1       0     130     .07       0  254.29      .1       0
  344.29     .07       0  354.29     .08       0  454.29     .06       0
   455.2    .045       0  471.48     .06       0  554.29      .1       0
#XS Ineff= 2 , 0
           169.6  833.46
Permanent Ineff=
       F       F
Bank Sta=455.2,471.48
XS Rating Curve= 0 ,0
Exp/Cntr(USF)=0,0
Exp/Cntr=0.3,0.1

Type RM Length L Ch R = 1 ,13530   ,30.2,30.2,30.3
XS GIS Cut Line= 3
1647919.78513101367806.8579274761647996.81889051367715.492305746
1648555.76151756367796.109030802
#Sta/Elev= 30
       0  863.65    18.7  853.91    39.7  836.91    50.1  831.75    76.3  829.93
    99.8  824.92   118.4  823.27   219.8  822.92   244.9  820.72   276.4  821.09
   328.9  817.49   349.2  817.94   374.1  811.59   381.2  811.06  390.48   811.6
   401.7  818.58   405.7   819.4     434  819.22   438.1  820.57   458.3  838.22
   470.4  842.67   490.6  859.96   518.9  878.97   535.1  886.59   567.4  905.94
   591.6  916.38   607.8  927.54     624  930.77   636.1  939.96684.2332  962.59
#Mann= 7 ,-1,0
       0     .06       0     110     .05       0  189.51     .07       0
  289.51      .1       0   374.1    .045       0  390.48     .06       0
  489.51      .1       0
Bank Sta=374.1,390.48
XS Rating Curve= 0 ,0
Exp/Cntr(USF)=0,0
Exp/Cntr=0.3,0.1

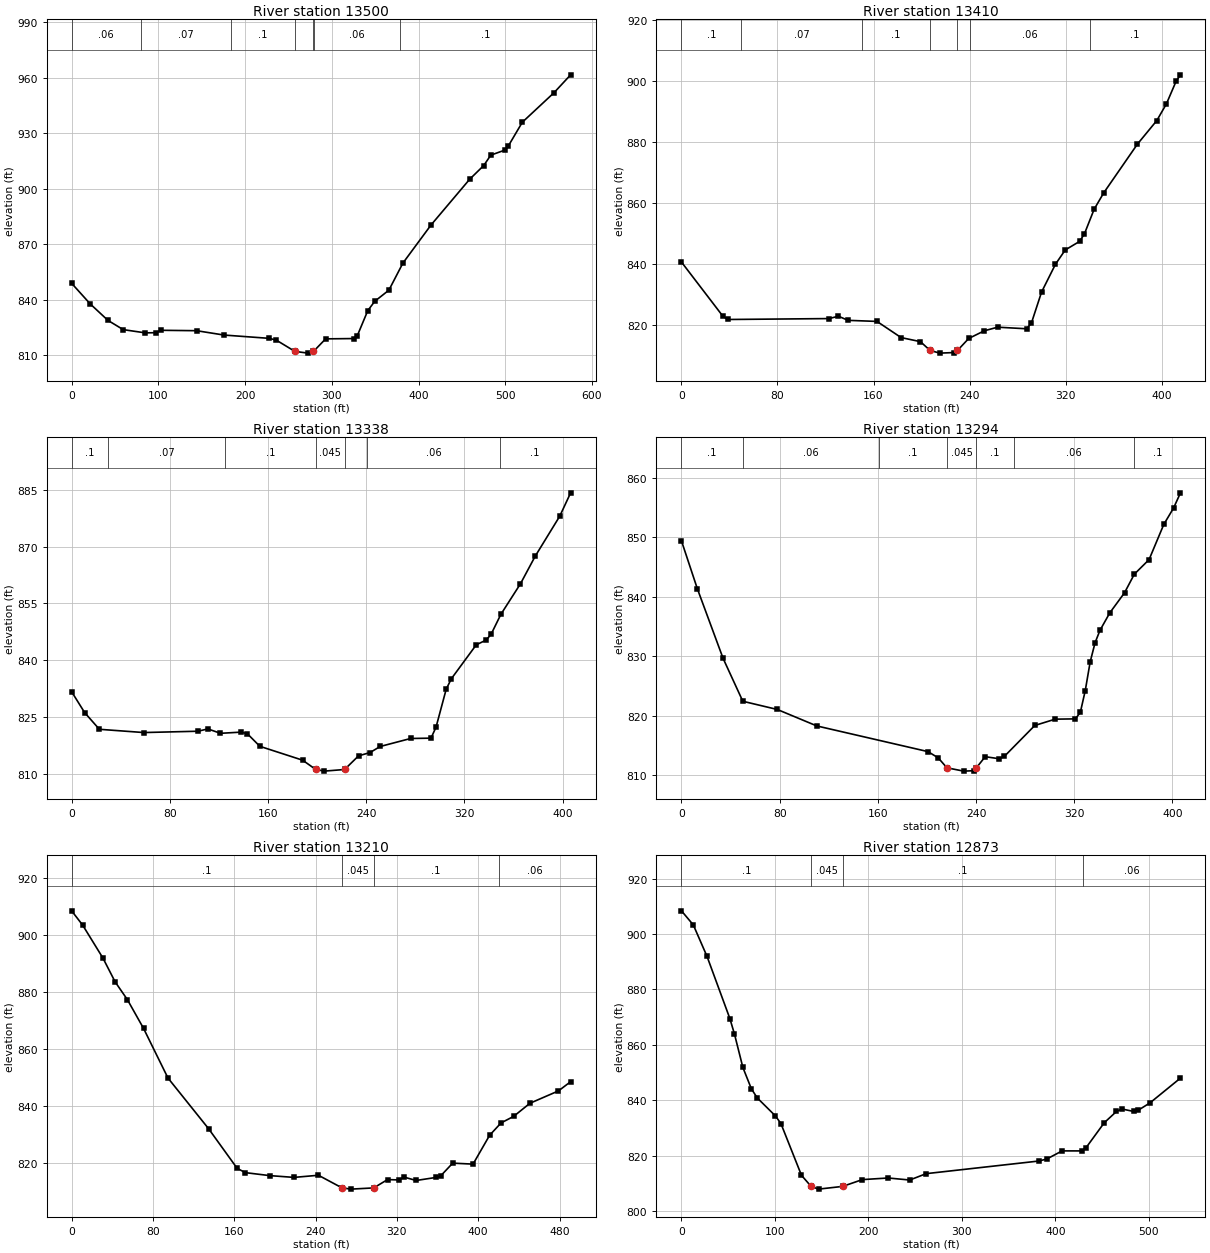
Type RM Length L Ch R = 1 ,13500   ,91.2,90.4,89.8
XS GIS Cut Line= 6
1647997.99085986367822.7946616891648129.18359642367763.139443845
 1648301.9946025367790.7309240851648376.05646226367802.556031674
1648462.46212934367816.3516077551648555.05151109367831.059583589
#Sta/Elev= 30
       0  848.79    21.4  837.65    41.9  828.71    59.5  823.71    84.9  821.96
    96.9  822.05   103.4  823.35   144.1  823.13   175.8  820.77   228.1  818.98
   236.2  817.97   257.5  811.91   272.7  810.99  278.86  811.91   292.9  818.71
   325.3  818.88   329.4  820.41   341.5  834.02   349.6  839.08   365.8  845.06
     382  859.74   414.4  880.35     459  905.13   475.2  912.55   483.3  918.15
   499.5  920.88   503.5   923.1   519.7  935.99   556.2  951.95575.3691  961.63
#Mann= 7 ,-1,0
       0     .06       0      80     .07       0  184.12      .1       0
   257.5    .045       0  278.86      .1       0  279.12     .06       0
  379.12      .1       0
Bank Sta=257.5,278.86
XS Rating Curve= 0 ,0
Exp/Cntr(USF)=0,0
Exp/Cntr=0.3,0.1

Type RM Length L Ch R = 1 ,13410   ,69.4,71.5,73.4
XS GIS Cut Line= 2
1648021.89964941367851.6449969521648435.73217137 367891.05761809
#Sta/Elev= 30
       0  840.54    34.4  822.85    38.4  821.71   122.8  822.01   130.8  822.78
   138.8  821.43   162.9  821.08     183  815.78   199.1  814.45   207.1  811.57
   215.2  810.69   227.2  810.88  229.94  811.56   239.3  815.49   252.3  818.01
   263.4  819.19   287.5  818.67   291.5  820.49     300  830.71   311.6  839.83
   319.7  844.49   331.7  847.31   335.7  849.77   343.8  857.84   351.8  863.22
   379.9   879.2     396   886.9     404  892.37   412.1   899.8415.7051  901.88
#Mann= 7 ,-1,0
       0      .1       0      50     .07       0     150      .1       0
   207.1    .045       0  229.94      .1       0     240     .06       0
     340      .1       0
Bank Sta=207.1,229.94
XS Rating Curve= 0 ,0
Exp/Cntr(USF)=0,0
Exp/Cntr=0.3,0.1

Type RM Length L Ch R = 1 ,13338   ,43.6,44.1,43.6
XS GIS Cut Line= 5
1648041.60595998367883.8916869741648156.26085784367894.640583649
 1648184.9245823367930.4702392291648337.20061852367971.674343146
1648424.98327469367971.674343146
#Sta/Elev= 30
       0  831.67    10.6  826.16    22.6  821.74    58.8  820.88     103  821.23
     111  821.84   121.3  820.68   138.1  820.99   143.2  820.56   153.4  817.24
   188.2  813.58  198.86  811.14   205.8  810.69   222.4  811.12   233.8  814.73
   243.1  815.59   251.4   817.2   276.2  819.31   292.8   819.4   296.9  822.29
   305.2  832.34   309.4   835.1   329.7  844.06   337.7   845.3   341.7  846.79
   349.7  852.08   365.7  860.18   377.7  867.45   397.7  878.03406.5769   884.2
#Mann= 7 ,-1,0
       0      .1       0      30     .07       0  125.16      .1       0
  198.86    .045       0   222.4      .1       0  241.04     .06       0
  348.79      .1       0
Bank Sta=198.86,222.4
XS Rating Curve= 0 ,0
Exp/Cntr(USF)=0,0
Exp/Cntr=0.3,0.1

Type RM Length L Ch R = 1 ,13294   ,88.3,84.2,82
XS GIS Cut Line= 5
1648018.31668385367922.4085667231648132.97158171367933.157463397
1648161.63530618367968.9871189781648313.91134239368010.191222895
1648401.69399857368010.191222895
#Sta/Elev= 30
       0  849.42    12.9  841.39    33.9  829.66      50  822.43    78.1  821.05
   110.3  818.28   200.9  813.96   209.2  812.91   216.3  811.24   229.9  810.68
   238.2  810.75  240.27  811.23   247.5  813.11   258.9  812.76   263.1  813.16
   287.9  818.36   304.5  819.42     321  819.47     325  820.57     329  824.22
     333  829.04     337  832.28     341  834.36     349   837.3     361  840.68
     369  843.81     381  846.26     393  852.18     401  854.95406.5769  857.49
#Mann= 7 ,-1,0
       0      .1       0      50     .06       0  161.04      .1       0
   216.3    .045       0  240.27      .1       0  271.04     .06       0
  368.79      .1       0
Bank Sta=216.3,240.27
XS Rating Curve= 0 ,0
Exp/Cntr(USF)=0,0
Exp/Cntr=0.3,0.1

Type RM Length L Ch R = 1 ,13210   ,345.4,337.1,324.4
XS GIS Cut Line= 2
1647941.28292436368068.4144132141648432.14920581368073.788861551
#Sta/Elev= 30
       0  908.62    10.8  903.62    30.8     892    42.8  883.62    54.8  877.39
    70.8  867.21    94.8  849.76   134.8   831.9   162.8     818   170.8  816.47
   194.8  815.42   218.8  814.79   242.8  815.54  265.96  811.11   274.8  810.66
   297.2  811.09   310.8  814.02   322.3  813.89   326.9  814.91   338.9   813.7
   358.9   814.8   362.9  815.26   374.9  819.81   394.9  819.46   411.2  829.61
   422.4  833.95   434.9  836.28   450.9  840.89   478.9  845.23   490.9  848.48
#Mann= 4 ,-1,0
       0      .1       0  265.96    .045       0   297.2      .1       0
     420     .06       0
Bank Sta=265.96,297.2
XS Rating Curve= 0 ,0
Exp/Cntr(USF)=0,0
Exp/Cntr=0.3,0.1

Type RM Length L Ch R = 1 ,12873   ,373,372.7,371.9
XS GIS Cut Line= 2
1648109.68230558368482.2469351681648546.80410367368175.903379955
#Sta/Elev= 30
       0  908.36    12.7  903.27    27.4  891.87    51.8  869.45    56.7  863.88
    65.7   851.8    74.8  844.09    81.1  840.79   100.6  834.27   106.4  831.54
   128.4  812.84  138.69  808.85   146.6  807.86   172.4  808.84   193.5   811.3
   221.2  811.88   244.2  811.15   261.8  813.45   382.1     818   390.7  818.72
   407.2  821.67     428  821.66   432.8  822.82   452.3  831.85   465.3   835.9
   471.1   836.8   483.9   835.9   488.3  836.29   501.2  839.01533.7807  847.96
#Mann= 4 ,-1,0
       0      .1       0  138.69    .045       0   172.4      .1       0
     430     .06       0
Bank Sta=138.69,172.4
XS Rating Curve= 0 ,0
Exp/Cntr(USF)=0,0
Exp/Cntr=0.3,0.1

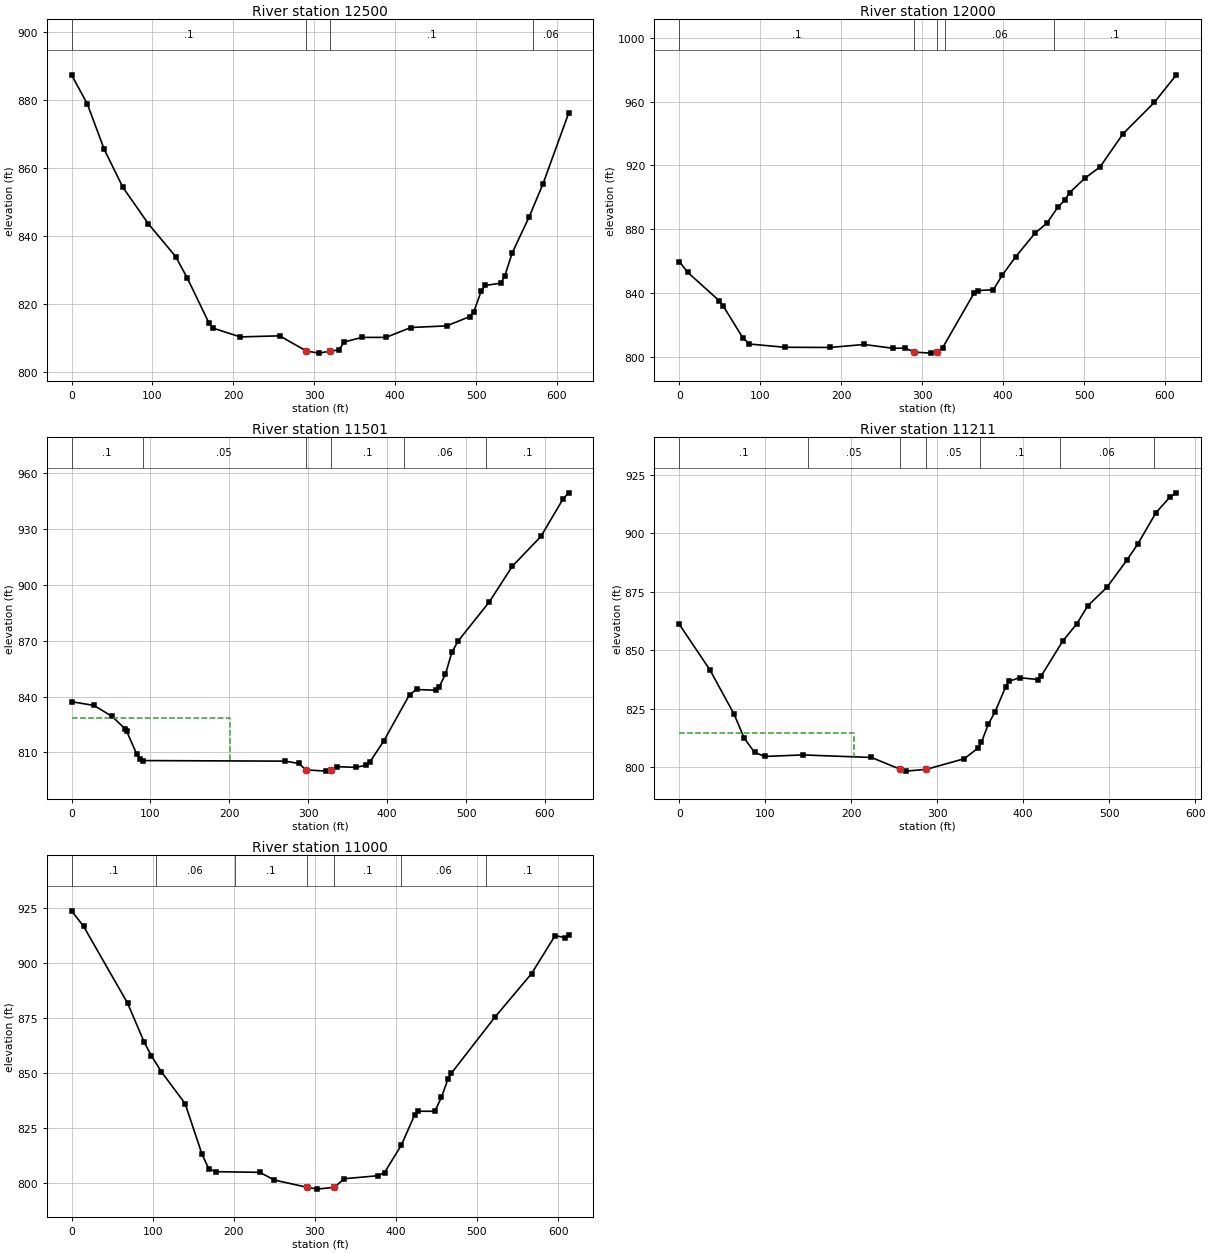
Type RM Length L Ch R = 1 ,12500   ,478.1,500.1,513.6
XS GIS Cut Line= 6
1648190.95512642368869.4115094991648276.66394451368828.146172091
1648485.61464208368669.2570541651648546.85106817 368625.88050051
1648619.53924301368576.912094504 1648698.7067356368526.139558256
#Sta/Elev= 30
       0  887.51    19.5  878.96    40.5  865.54    63.4  854.44    95.1  843.64
   128.7  834.04     143  827.76   169.8  814.53   174.8  812.99   208.6  810.39
   257.2  810.71   290.4  806.23   305.7  805.62     320  806.21   330.6  806.57
   337.1   808.9   358.9  810.25   388.6  810.25   419.5  813.16   463.7  813.64
   492.2  816.36   496.9  817.59   506.5  823.93   511.4  825.53   530.5  826.21
   535.3  828.17   544.8  835.18   565.5  845.62   582.8  855.45614.3617  876.16
#Mann= 4 ,-1,0
       0      .1       0   290.4    .045       0     320      .1       0
  570.31     .06       0
Bank Sta=290.4,320
XS Rating Curve= 0 ,0
Exp/Cntr(USF)=0,0
Exp/Cntr=0.3,0.1

Type RM Length L Ch R = 1 ,12000   ,512.6,499.3,477.2
XS GIS Cut Line= 6
1648183.64871059368964.6009516721648262.05078475369018.525384501
1648337.16874476369063.5912392591648401.45962667 369102.36314334
1648486.56509951369154.9243899291648704.14504492369290.066836178
#Sta/Elev= 30
       0  859.87    10.3  853.09    49.1   835.4      54  832.23    78.2  812.26
    86.6  808.19   130.2  806.16   186.2  806.04   228.2   807.9   264.2  805.51
   278.8  805.64   290.4  803.12   310.7  802.49  318.87  803.12   325.3  805.88
   364.4  840.36   369.1  841.68   387.9  842.18   398.8  851.18   415.3  862.74
   439.7  877.77   453.9  883.74   467.6  893.92   476.3  898.38   482.1  903.03
   500.9  911.99   519.8  919.15     548  939.78   586.7  959.45     614  976.77
#Mann= 5 ,-1,0
       0      .1       0   290.4    .045       0  318.87      .1       0
  327.83     .06       0  462.83      .1       0
Bank Sta=290.4,318.87
XS Rating Curve= 0 ,0
Exp/Cntr(USF)=0,0
Exp/Cntr=0.3,0.1

Type RM Length L Ch R = 1 ,11501   ,281.2,289.1,298.8
XS GIS Cut Line= 6
1647976.67963634369652.3584344241648153.81543693369599.425797507
 1648223.6053236369569.8254630121648374.56073034369481.252477422
 1648464.9808251369467.3820983321648567.01900683369477.850253254
#Sta/Elev= 30
       0  837.29    28.4  835.29    51.5  829.36    67.8  822.74    69.9  821.39
    82.4  809.37    86.5  806.69    90.7  805.65   270.5  805.35   288.2  804.11
   296.9  800.66   323.1  799.98  329.38  800.68   336.4  802.38   360.9  801.98
   373.6  803.27   378.2  804.91   395.9  816.36   428.4  841.14   437.4  843.85
   461.7  843.44   465.7  845.08   473.8  852.01   481.9  863.75     490  869.95
   529.5  890.97   558.6  910.08   594.8   926.1   622.9  946.27629.8551  949.54
#Mann= 6 ,-1,0
       0      .1       0      90     .05       0   296.9    .045       0
  329.38      .1       0  420.74     .06       0   525.8      .1       0
#XS Ineff= 2 , 0
          201.21  828.31
Permanent Ineff=
       F       F
Bank Sta=296.9,329.38
XS Rating Curve= 0 ,0
Exp/Cntr(USF)=0,0
Exp/Cntr=0.3,0.1

Type RM Length L Ch R = 1 ,11211   ,214.4,211.4,206.7
XS GIS Cut Line= 3
1648016.62625889369831.9487952941648399.28160604369828.030822457
1648587.34430225369774.485193675
#Sta/Elev= 30
       0  861.05    35.5  841.67    63.5  822.87    75.5  812.51    87.5  806.42
    99.5  804.68   143.5  805.33   223.5  804.25   257.1   799.2   263.5  798.42
   287.5  799.19   331.5  803.72   347.4  808.24   351.5  810.75   359.5   818.5
   367.2  823.66   379.5  834.27   383.5  836.75   395.9  838.31   416.8   837.5
     421  839.04   445.9  853.84   462.6   861.4     475   868.9   497.7  876.99
   520.8  888.55   533.3  895.34   554.5  908.73   570.7  915.38578.2124   917.2
#Mann= 7 ,-1,0
       0      .1       0     150     .05       0   257.1    .045       0
   287.5     .05       0     350      .1       0  442.68     .06       0
  552.68      .1       0
#XS Ineff= 2 , 0
          202.86  814.49
Permanent Ineff=
       F       F
Bank Sta=257.1,287.5
XS Rating Curve= 0 ,0
Exp/Cntr(USF)=0,0
Exp/Cntr=0.3,0.1

Type RM Length L Ch R = 1 ,11000   ,484.8,500.6,510.5
XS GIS Cut Line= 6
1648069.93305875370110.0606030081648159.72881092370083.120040089
1648411.15809809370007.6907290071648483.91582659369989.208810583
1648569.16204718369968.8712528351648660.26619567369945.878188595
#Sta/Elev= 30
       0  923.81    14.8  916.81    69.1  881.84    89.7  864.02    98.3  858.01
   110.9  850.58   140.1  836.14     161  813.03   169.3   806.5   177.7  805.19
     232   804.9   250.3  801.37   290.4  798.11     303  797.26  324.01  798.11
   336.4     802   377.9  803.35     386   804.8   406.8  817.33   423.3  831.15
   427.4  832.69     448  832.65   456.2  839.05   464.4  847.54   468.5  850.02
     522  875.42   567.4  895.31   596.3  912.54   608.6  911.63 612.918  912.89
#Mann= 7 ,-1,0
       0      .1       0  103.75     .06       0  201.25      .1       0
   290.4    .045       0  324.01      .1       0  406.25     .06       0
  511.32      .1       0
Bank Sta=290.4,324.01
XS Rating Curve= 0 ,0
Exp/Cntr(USF)=0,0
Exp/Cntr=0.3,0.1