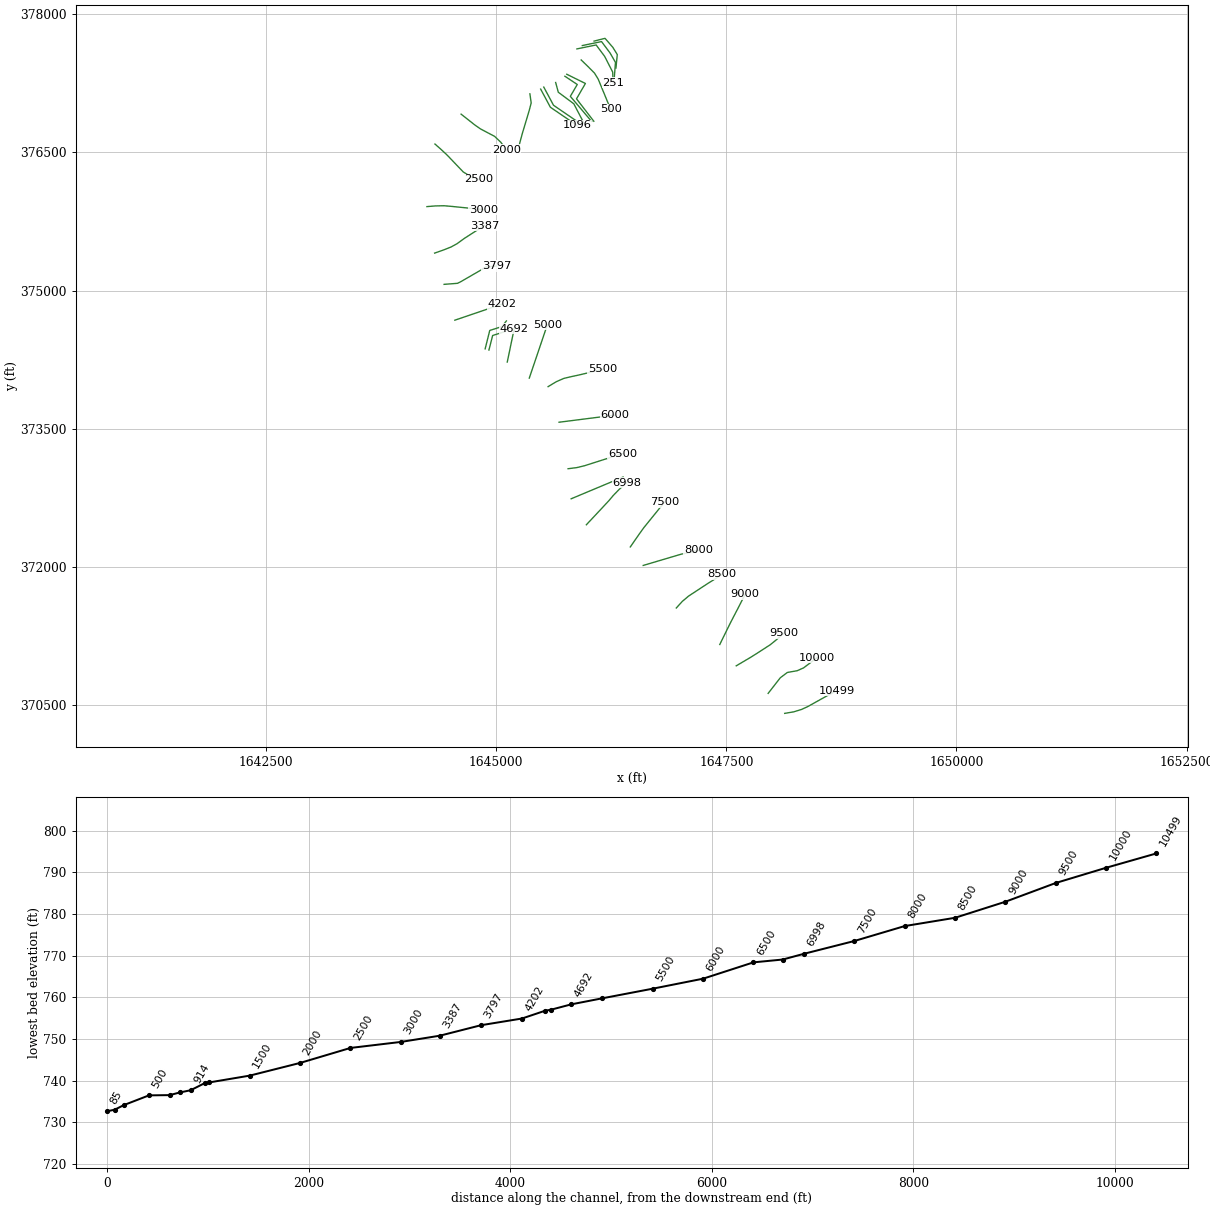
HEC-RAS study BUFFALORN.prj: BUFFALORN

--- BUFFALORN.g01 (geometry) --- (continued)

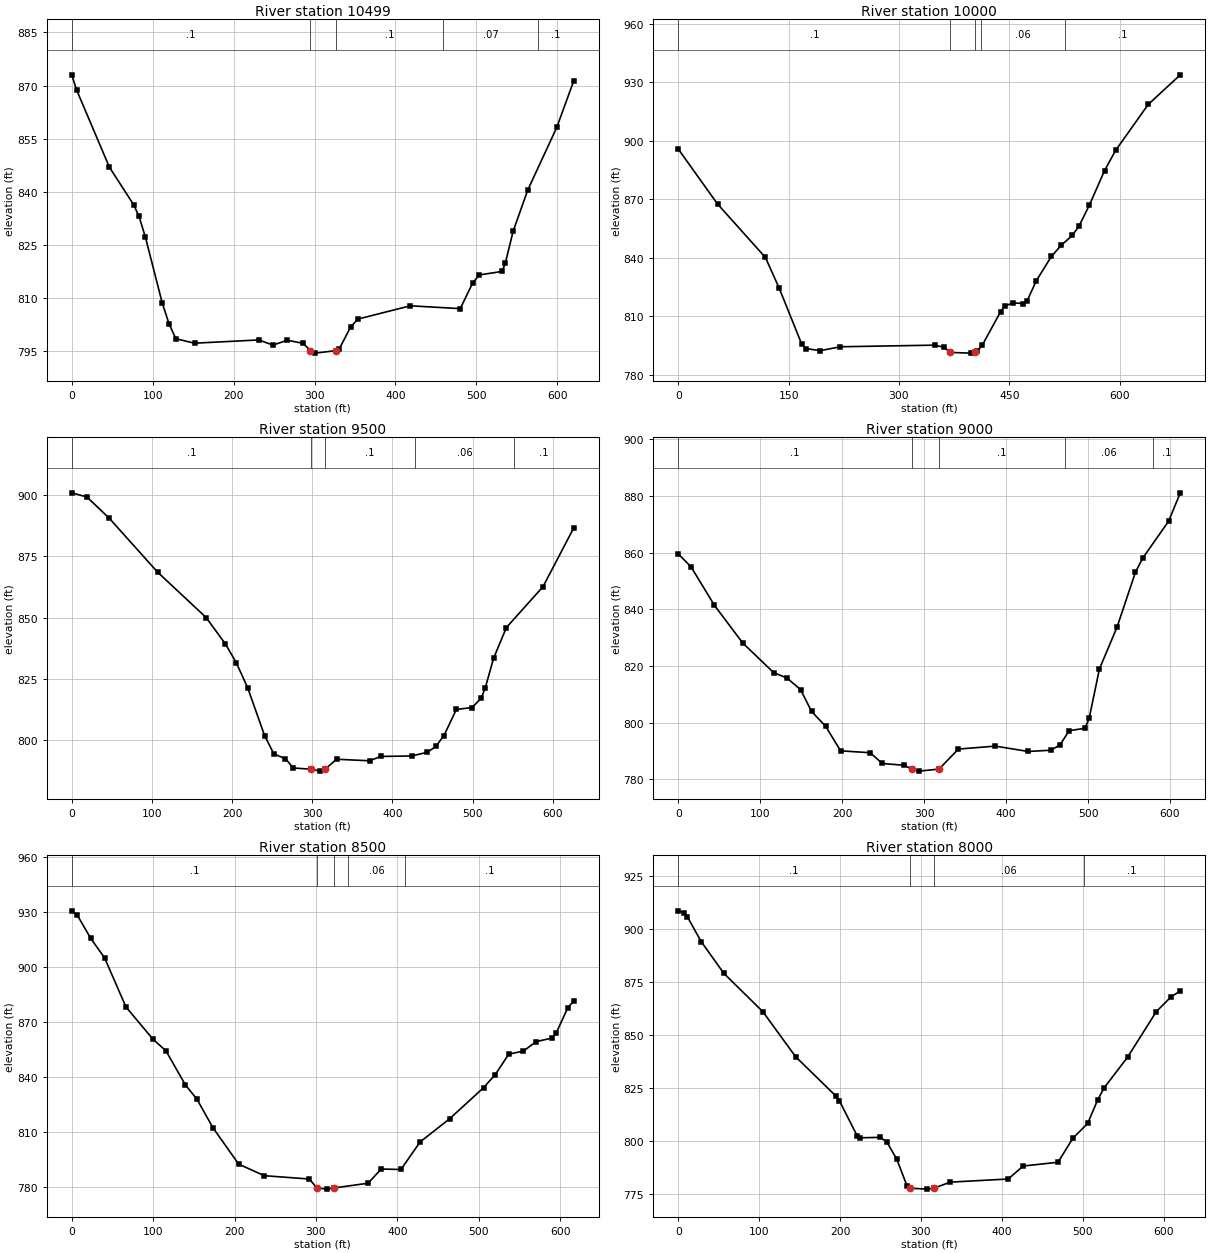
Type RM Length L Ch R = 1 ,10499   ,493.1,498.9,476.6
XS GIS Cut Line= 6
1648134.25937368 370406.331992091648230.86187075370422.704662755
1648317.14581892370448.9503451731648386.13911925370480.864651427
1648615.35060309370608.8089493361648698.88914992370651.530320585
#Sta/Elev= 30
       0  873.03     5.9   868.8    46.5  846.98    76.4  836.42      83  833.18
    91.1  827.18   111.8   808.7   120.2  802.82   128.6  798.61   151.7  797.34
   231.1  798.26   248.7   796.8   266.4  798.18     286  797.29  294.95  795.25
   300.8  794.54  326.94  795.25   330.7  795.78   344.9  802.01   353.8  804.15
   418.4  807.89   480.1  807.09   495.4  814.27   503.6   816.6     532  817.58
     536  820.07   545.5  828.92   563.5  840.51   599.4   858.2620.5201  871.41
#Mann= 5 ,-1,0
       0      .1       0  294.95    .045       0  326.94      .1       0
  459.19     .07       0  576.69      .1       0
Bank Sta=294.95,326.94
XS Rating Curve= 0 ,0
Exp/Cntr(USF)=0,0
Exp/Cntr=0.3,0.1

Type RM Length L Ch R = 1 ,10000   ,505.5,500.5,519.6
XS GIS Cut Line= 6
1647954.40540268370623.7396937611648086.75717209370793.526099592
1648163.13858101370850.9114835111648270.28469217370869.864529595
1648339.59951417370900.9596117591648488.58740517371013.268114179
#Sta/Elev= 30
       0   895.7    53.4  867.52   118.5  840.13   137.1   824.5     168  795.58
   173.1  793.45   193.2  792.38   220.5  794.36   348.5  795.19   360.7  794.16
  370.01  791.45   397.3   791.1     403  791.44   406.4  792.09   413.3   795.2
   438.3  812.43   443.7  815.24   455.6  816.87   468.6  816.51   474.4  818.04
   486.8  828.25   507.3  840.71   520.8  846.42   535.5   851.4   544.7  856.14
     559  867.08   579.4  884.57   594.5  894.99   638.9  918.56682.4477  933.71
#Mann= 5 ,-1,0
       0      .1       0  370.01    .045       0     403      .1       0
  410.99     .06       0  525.76      .1       0
Bank Sta=370.01,403
XS Rating Curve= 0 ,0
Exp/Cntr(USF)=0,0
Exp/Cntr=0.3,0.1

Type RM Length L Ch R = 1 ,9500    ,487.2,499.5,503.9
XS GIS Cut Line= 6
1647607.72532175370922.9694102561647764.95171334 371015.70675759
1647828.44371234371055.7444071771647975.45030808371150.687130675
1648044.86552359 371206.718842761648123.26595734371275.773822755
#Sta/Elev= 30
       0  900.91      19  899.19    46.8  890.53     107  868.59   167.6  850.07
   191.6  839.31   205.2  831.67   219.4  821.44   240.5  801.96   252.1  794.45
   266.6   792.5   276.3  788.73   298.4  788.22     310  787.44  315.94  788.21
   330.3  792.29   371.5  791.65   385.2  793.43   423.9  793.62   443.7  795.14
   454.3  797.56   464.3  801.96   479.7  812.58   499.2  813.35   510.6  817.11
   515.7  821.28   526.1   833.4   542.1  845.97   587.8  862.65626.2862  886.68
#Mann= 5 ,-1,0
       0      .1       0   298.4    .045       0  315.94      .1       0
   427.6     .06       0  551.81      .1       0
Bank Sta=298.4,315.94
XS Rating Curve= 0 ,0
Exp/Cntr(USF)=0,0
Exp/Cntr=0.3,0.1

Type RM Length L Ch R = 1 ,9000    ,507.8,500.5,493.6
XS GIS Cut Line= 6
1647428.73945926371154.5558893381647508.69172718371317.297033668
1647541.93739559371384.5528046791647587.70141168371473.471262008
1647622.63310035371539.8398956661647704.93017983371701.323168501
#Sta/Elev= 30
       0  859.54    15.6  854.98      44  841.47    78.7  828.11   116.6  817.63
   132.5  815.81   149.3  811.67   162.6  804.03     180  798.68   198.1  790.09
   234.2  789.43     249  785.63   275.8     785   284.7  783.66   293.6  782.94
   318.2  783.65   341.8  790.72   386.9  791.76     427  789.87   454.6  790.31
   465.7  792.14     477  797.21   496.3  798.05   501.4  801.57   513.9  818.97
   535.4   833.7   557.8  853.04   566.7  858.04   598.2  871.01612.5934  881.07
#Mann= 5 ,-1,0
       0      .1       0   284.7    .045       0   318.2      .1       0
  471.35     .06       0  578.85      .1       0
Bank Sta=284.7,318.2
XS Rating Curve= 0 ,0
Exp/Cntr(USF)=0,0
Exp/Cntr=0.3,0.1

Type RM Length L Ch R = 1 ,8500    ,506.9,500,496.6
XS GIS Cut Line= 6
1646956.39657192 371551.347746671647021.51323959371622.660924256
1647088.89958775371679.7969648391647297.86406484371817.033567011
1647372.16181651371863.2818340961647450.25089918371916.430677921
#Sta/Elev= 30
       0  930.61       7  928.09    23.3   915.6    40.3  905.03    66.6  878.26
     100  860.58   115.7  854.41   139.5  835.89   153.7  828.11   173.5  812.48
   205.1  792.67   236.6  786.39   291.8  784.59  301.15  779.78   313.2  779.08
   322.8  779.77     364  782.28   380.2  790.03   404.4  789.77     428  804.76
   464.3   817.4   505.9  834.29   520.4  841.49   536.9  852.54     555   854.3
   570.8  859.42   590.1  861.33     595  863.88   609.5  877.87616.8945   881.6
#Mann= 5 ,-1,0
       0      .1       0  301.15    .045       0   322.8      .1       0
  339.92     .06       0  409.92      .1       0
Bank Sta=301.15,322.8
XS Rating Curve= 0 ,0
Exp/Cntr(USF)=0,0
Exp/Cntr=0.3,0.1

Type RM Length L Ch R = 1 ,8000    ,489.6,500,507.3
XS GIS Cut Line= 6
1646597.02622767372013.4921635841646770.78080143372065.075721845
1646938.54391734372114.880084172 1647010.4423956372136.225185841
1647098.04655109372152.6191819161647195.31472926372177.339933008
#Sta/Elev= 30
       0  908.46     7.4  907.53    11.4  905.59    28.3  893.98    56.4  878.94
   104.7  860.81   145.1   839.6   195.2  820.93   199.3  818.74   221.5  802.05
   224.4  801.31   249.4  801.53   257.7   799.5   270.3  791.11   282.8  778.66
  286.22  777.55   307.8  777.09   316.2  777.54   336.3  780.39     408  781.87
   426.4  787.99   469.6  789.78   487.8  801.08   506.2  808.09   518.6  819.25
   526.6  824.91   555.5  839.36   591.1  860.89   609.2  867.84 620.735  870.62
#Mann= 4 ,-1,0
       0      .1       0  286.22    .045       0   316.2     .06       0
  501.25      .1       0
Bank Sta=286.22,316.2
XS Rating Curve= 0 ,0
Exp/Cntr(USF)=0,0
Exp/Cntr=0.3,0.1

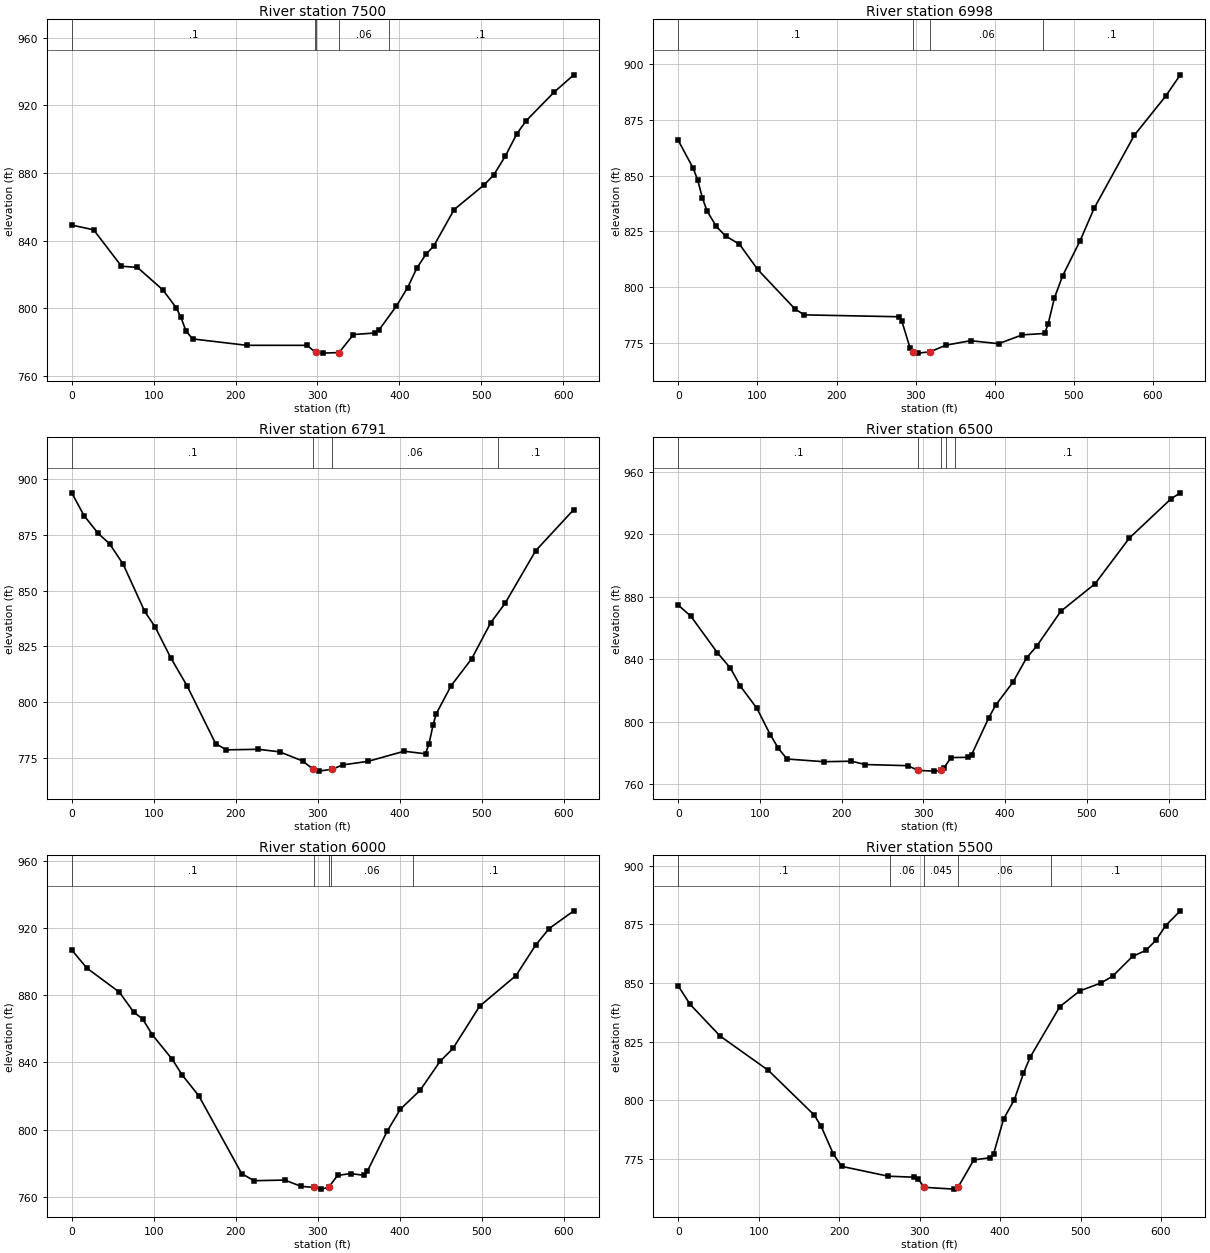
Type RM Length L Ch R = 1 ,7500    ,502.2,501.8,502.1
XS GIS Cut Line= 6
1646456.89330584372214.501932174 1646510.2071756372291.967984587
1646560.40228517372363.9173157511646604.35462509372424.835829094
1646667.31053592 372502.530883671646828.69866459372701.573464587
#Sta/Elev= 30
       0  849.18    26.7  846.38    60.7  824.85    80.2  824.15   111.4   810.8
   127.4  800.41   133.2  794.85   139.3  786.75   147.5   781.9   213.5  778.12
   287.4   778.1   297.7  773.88   307.3   773.5   326.4  773.85     344  784.48
   370.3   785.4   374.9  786.98   396.3  801.23   410.1  812.17   421.4  823.77
   432.8  832.11   441.9  836.67   466.9  858.32   503.7  872.98   515.3  878.79
   529.4  889.88   543.7  903.28   555.1  910.94   589.2   927.8613.1364  937.97
#Mann= 5 ,-1,0
       0      .1       0  296.89     .06       0   297.7    .045       0
   326.4     .06       0  386.89      .1       0
Bank Sta=297.7,326.4
XS Rating Curve= 0 ,0
Exp/Cntr(USF)=0,0
Exp/Cntr=0.3,0.1

Type RM Length L Ch R = 1 ,6998    ,211.4,207.6,202
XS GIS Cut Line= 6
1645979.21643968372455.2366869151646154.33551201372642.209082007
1646222.54108426372715.4251429291646271.05378251372772.978177428
1646335.88173684372839.9042246791646417.92487983372912.825338677
#Sta/Elev= 30
       0  865.84    18.9  853.33    24.7  847.92    30.6  839.96    36.4  834.18
    48.1  827.24    59.8  822.98    77.4  819.25   100.4  807.93   147.6   790.2
   159.3  787.58   278.9  786.73   282.3  785.05     293  772.66   296.2  771.02
   303.1  770.42  318.17     771   338.3  773.99   369.5     776   404.8  774.65
   434.8  778.61   463.1  779.25   467.5   783.6   475.4  795.22   485.7  805.07
   507.8  820.82   525.6  835.41   576.3  868.12     616  885.71 634.451  895.24
#Mann= 4 ,-1,0
       0      .1       0   296.2    .045       0  318.17     .06       0
  461.51      .1       0
Bank Sta=296.2,318.17
XS Rating Curve= 0 ,0
Exp/Cntr(USF)=0,0
Exp/Cntr=0.3,0.1

Type RM Length L Ch R = 1 ,6791    ,290.1,290.6,289.7
XS GIS Cut Line= 2
1645814.40876094372737.8413906081646378.88706978372974.370861922
#Sta/Elev= 30
       0  893.88    14.9  883.68    32.2  875.67    46.2  870.98    62.6  861.89
    88.9  840.69   101.6  833.72   120.8  819.79   140.6  807.28   175.3  781.44
   188.3   778.6   227.4  778.85   253.4  777.71   281.5   773.6  294.14  769.92
   301.1  769.06   317.5  769.91   330.4  771.86     361  773.43   405.2  777.98
   431.2  776.84   435.5  781.36   440.4  789.68   444.2  794.73   462.4  807.35
   487.6  819.52   510.7  835.61   528.2  844.32   565.5  867.92 612.031   886.4
#Mann= 4 ,-1,0
       0      .1       0  294.14    .045       0   317.5     .06       0
     520      .1       0
Bank Sta=294.14,317.5
XS Rating Curve= 0 ,0
Exp/Cntr(USF)=0,0
Exp/Cntr=0.3,0.1

Type RM Length L Ch R = 1 ,6500    ,501.9,500,497.6
XS GIS Cut Line= 6
 1645780.7240545373064.3604686711645875.32261859373076.438200429
1645960.57540084373097.1097470071646127.27651101 373150.36062476
1646198.71993767373173.182757586 1646371.3747761373228.335862502
#Sta/Elev= 30
       0  874.74    15.5  867.58    47.8   844.3    63.9  834.33      76  822.82
    96.2  808.67   112.6  791.78   122.6  782.88   133.2  776.14   178.5  774.41
     212  774.74   228.8   772.6   280.9  771.87   293.7  768.85   312.7  768.38
  321.54  768.83   325.4  770.63   333.8  777.08   354.8  777.21     359  778.95
     380  802.62   388.4  810.63   409.4  825.23   426.2   840.9   438.8  848.56
   468.1  870.77   510.1  888.45   552.1  917.73   602.8  942.74614.3394  946.66
#Mann= 5 ,-1,0
       0      .1       0   293.7    .045       0  321.54      .1       0
  328.09     .06       0  338.09      .1       0
Bank Sta=293.7,321.54
XS Rating Curve= 0 ,0
Exp/Cntr(USF)=0,0
Exp/Cntr=0.3,0.1

Type RM Length L Ch R = 1 ,6000    ,498,499.6,496.4
XS GIS Cut Line= 6
1645682.49787301 373569.455259011645775.49768701373581.292505667
1645862.29738218 373592.339727671646110.29688618373623.904297084
1646197.09658134373634.9515190871646290.09639534373646.788109586
#Sta/Elev= 30
       0     907    18.5  896.22    58.1  881.87    75.7   869.9    86.3  866.01
    98.4  856.42   122.6  841.83   134.7  832.52   154.9  820.15   207.3   773.7
   222.4  769.48   259.7  769.86   279.9  766.12     296  765.47     304  764.46
  313.26  765.46   324.2  772.61   340.2  773.75   356.5  772.69   360.5  775.07
   384.7  798.92   400.8  812.05     425  823.42   449.2   840.6     465  848.31
   497.6  873.54     542  891.83   565.8  909.87   582.3   919.8612.5001  930.39
#Mann= 5 ,-1,0
       0      .1       0     296    .045       0  313.26      .1       0
  316.25     .06       0  416.25      .1       0
Bank Sta=296,313.26
XS Rating Curve= 0 ,0
Exp/Cntr(USF)=0,0
Exp/Cntr=0.3,0.1

Type RM Length L Ch R = 1 ,5500    ,487.2,500.4,527
XS GIS Cut Line= 6
1645563.51221859373956.040443838 1645651.8936035374009.184038341
1645733.84455509 374045.402141751645806.82931726 374062.80400984
1645904.55943675374084.0054109991646153.79450259374143.308113918
#Sta/Elev= 30
       0  848.74    14.7   840.9      52  827.37   112.1  812.69     169  793.66
   177.7  788.79   192.7  777.06   203.3  771.76   260.9  767.58   293.6  767.13
   297.7  766.59   305.7  762.83   342.7  762.06   347.7  762.84   367.3  774.51
   387.9  775.48     392  777.19   404.3  791.93   417.7  800.23     429  811.42
   437.2  818.26   474.2   839.9   498.9   846.6   525.6  850.03     540  852.95
   564.7  861.38   581.1  863.87   593.7  868.26   605.8   874.5623.9533  880.78
#Mann= 5 ,-1,0
       0      .1       0  262.73     .06       0   305.7    .045       0
   347.7     .06       0  462.76      .1       0
Bank Sta=305.7,347.7
XS Rating Curve= 0 ,0
Exp/Cntr(USF)=0,0
Exp/Cntr=0.3,0.1

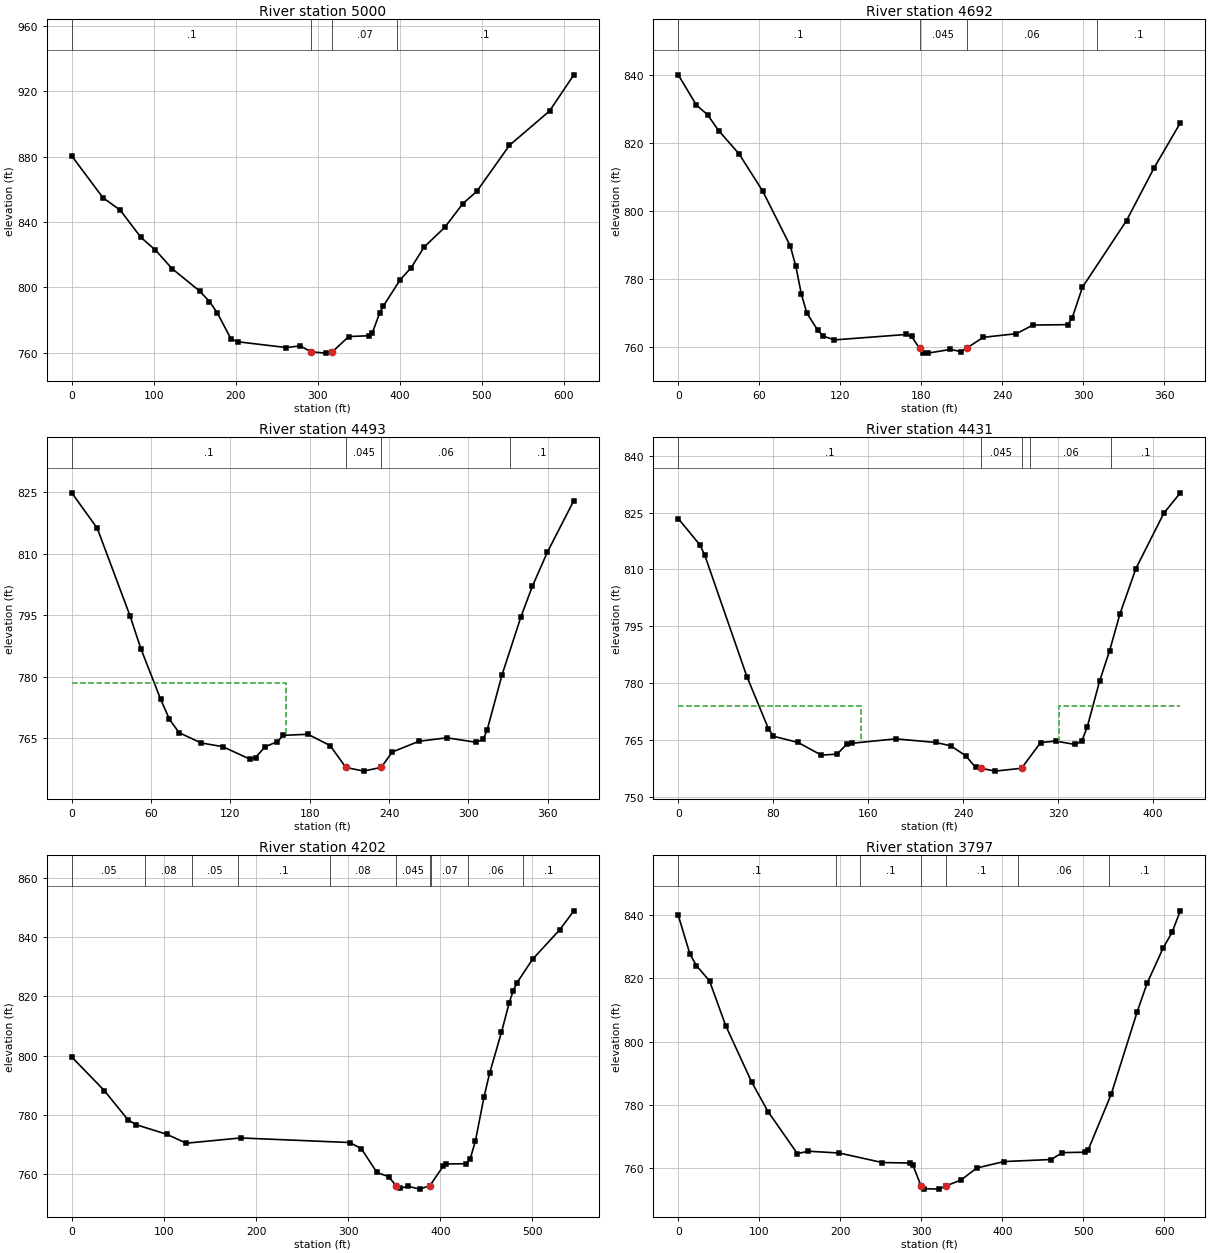
Type RM Length L Ch R = 1 ,5000    ,306.1,307.8,309.6
XS GIS Cut Line= 6
1645359.06708942374048.5556787551645417.21362667374220.225282922
1645441.27460217374291.2612300961645497.41589409374457.011554763
 1645525.4867041374539.8863890021645555.56308751374628.681158915
#Sta/Elev= 30
       0   880.4      38  854.85    59.1  847.23    84.4  830.54   101.8  822.94
   122.5  811.38   156.2  797.64     168  791.27   177.4   784.5   194.2  768.47
   202.7  766.69   261.8  763.16   278.7  764.18   292.1  760.53     310  759.75
  317.93  760.54   337.8  769.89   363.2   770.4   366.8  772.28   375.8  784.58
   380.1   788.5   400.6  804.63   413.9  811.91   429.8  824.64   455.1  836.74
   477.2  851.29   494.1  858.72     534  886.93   582.8  907.85   612.5  930.02
#Mann= 4 ,-1,0
       0      .1       0   292.1    .045       0  317.93     .07       0
  396.25      .1       0
Bank Sta=292.1,317.93
XS Rating Curve= 0 ,0
Exp/Cntr(USF)=0,0
Exp/Cntr=0.3,0.1

Type RM Length L Ch R = 1 ,4692    ,210.8,198.7,178.4
XS GIS Cut Line= 2
1645120.06749282374223.2748124231645195.70787683374587.542977491
#Sta/Elev= 30
       0  840.15    13.5  831.23    21.7  828.43    29.9  823.77    45.1  816.88
    62.6  805.95      83  789.83    87.1  783.92    91.2   775.7    95.3  770.08
   103.4  765.01   107.5   763.3   115.7  762.19   168.8  763.78   172.9   763.2
  178.78  759.74     181  758.46   185.1   758.3   201.5  759.38   209.6  758.77
   213.7  759.75     226  762.95   250.5  764.01   262.8  766.55   288.7  766.68
     292  768.76   299.5  777.67   332.2  797.29   352.6  812.78372.0387  826.01
#Mann= 4 ,-1,0
       0      .1       0  178.78    .045       0   213.7     .06       0
     310      .1       0
Bank Sta=178.78,213.7
XS Rating Curve= 0 ,0
Exp/Cntr(USF)=0,0
Exp/Cntr=0.3,0.1

Type RM Length L Ch R = 1 ,4493    ,62.4,62.2,61.8
XS GIS Cut Line= 4
1644920.89441852374353.8739070141644961.20278105374511.882688124
1645093.41421014374553.8033851531645141.78424518374615.072096195
#Sta/Elev= 30
       0  824.84    19.3  816.19      44  794.92    52.3  786.84    67.3  774.49
    73.9  769.65    81.2   766.4    97.7  763.91   114.2  762.99   134.8  759.95
     139  760.35   146.3  762.97   155.5  764.21   159.9  765.75   178.7  766.01
   195.5  763.24   207.3  757.94   220.7  757.03   234.1  757.95   242.4  761.68
   262.6   764.3   283.8  765.15   306.1  764.05   311.3  764.87   314.2  767.04
   325.5  780.51   339.8  794.65   348.4  802.06   359.7  810.33   379.8  822.96
#Mann= 4 ,-1,0
       0      .1       0   207.3    .045       0   234.1     .06       0
  331.77      .1       0
#XS Ineff= 2 , 0
          162.11  778.53
Permanent Ineff=
       F       F
Bank Sta=207.3,234.1
XS Rating Curve= 0 ,0
Exp/Cntr(USF)=0,0
Exp/Cntr=0.3,0.1

Type RM Length L Ch R = 1 ,4431    ,229.7,229.5,230.3
XS GIS Cut Line= 4
1644879.77988875374366.7725830231644929.76225828374566.702061162
1645061.97368737374608.6227581911645110.34372241374669.891469233
#Sta/Elev= 30
       0  823.41    18.3  816.45    22.4   813.7    57.8  781.72      76  767.93
    80.2  765.96   100.8  764.34   120.5  760.98   133.8  761.25     142  763.91
   146.1  764.11   183.2  765.28   216.9  764.32   229.5  763.44   242.1  760.81
   250.5  757.74   254.7  757.53   266.8  756.76   289.1  757.51   305.1  764.28
   317.7  764.69   334.4  763.79     340  764.77   344.5   768.5   354.8  780.48
   363.3  788.59   371.9  798.19   385.4  810.22   408.9  824.82   422.8  830.21
#Mann= 5 ,-1,0
       0      .1       0   254.7    .045       0   289.1      .1       0
  296.08     .06       0  364.78      .1       0
#XS Ineff= 2 , 0
          154.19  773.82  320.48          773.82
Permanent Ineff=
       F       F
Bank Sta=254.7,289.1
XS Rating Curve= 0 ,0
Exp/Cntr(USF)=0,0
Exp/Cntr=0.3,0.1

Type RM Length L Ch R = 1 ,4202    ,401.4,405.1,408.1
XS GIS Cut Line= 2
1644550.57502274374678.112384652 1645066.5220631374853.677696997
#Sta/Elev= 30
       0  799.52    35.4  788.17    60.8  778.39    69.3  776.71     103  773.44
   124.2  770.41   183.3  772.18   301.6  770.64   314.3  768.59   331.2  760.53
   343.9  759.11  351.97  756.07   356.5  755.14     365  755.86   377.7  754.89
  388.72  756.07     403  762.57   406.6  763.39   428.4  763.48   432.6  765.21
   438.2  771.26   447.6  786.17   453.7  794.22   466.4  807.86   474.9   817.9
   479.1  821.85   483.3  824.64   500.2  832.57   529.8  842.58544.9996  848.93
#Mann= 10 ,-1,0
       0     .05       0      80     .08       0     130     .05       0
     180      .1       0     280     .08       0  351.97    .045       0
  388.72     .08       0     390     .07       0     430     .06       0
     490      .1       0
Bank Sta=351.97,388.72
XS Rating Curve= 0 ,0
Exp/Cntr(USF)=0,0
Exp/Cntr=0.3,0.1

Type RM Length L Ch R = 1 ,3797    ,407.2,409.3,408.2
XS GIS Cut Line= 6
1644433.63769649375067.4835808311644579.28019246 375078.60002559
1644613.81478221375095.5439692441644830.21198721375220.733023316
1644888.03618116375255.5917947621645005.01429651375266.708567599
#Sta/Elev= 30
       0  840.01    14.5  827.66    22.5  824.03    38.6  819.24    58.6  805.04
    90.7  787.16   110.8  777.85     147  764.53   160.4   765.3   198.7  764.72
   251.9   761.7   286.5  761.56   289.4  761.03  299.61  754.31   302.7  753.45
   321.6  753.29   330.4  754.32   348.9  756.16   368.4  759.98   402.2  762.02
   460.1  762.67   474.1  764.84   502.1  764.99   506.1  765.83   534.3  783.32
   566.4  809.46   578.5   818.4   598.6  829.74   609.4  834.59   619.6  841.41
#Mann= 7 ,-1,0
       0      .1       0  194.53     .05       0  224.53      .1       0
  299.61    .045       0   330.4      .1       0  419.53     .06       0
  532.05      .1       0
Bank Sta=299.61,330.4
XS Rating Curve= 0 ,0
Exp/Cntr(USF)=0,0
Exp/Cntr=0.3,0.1

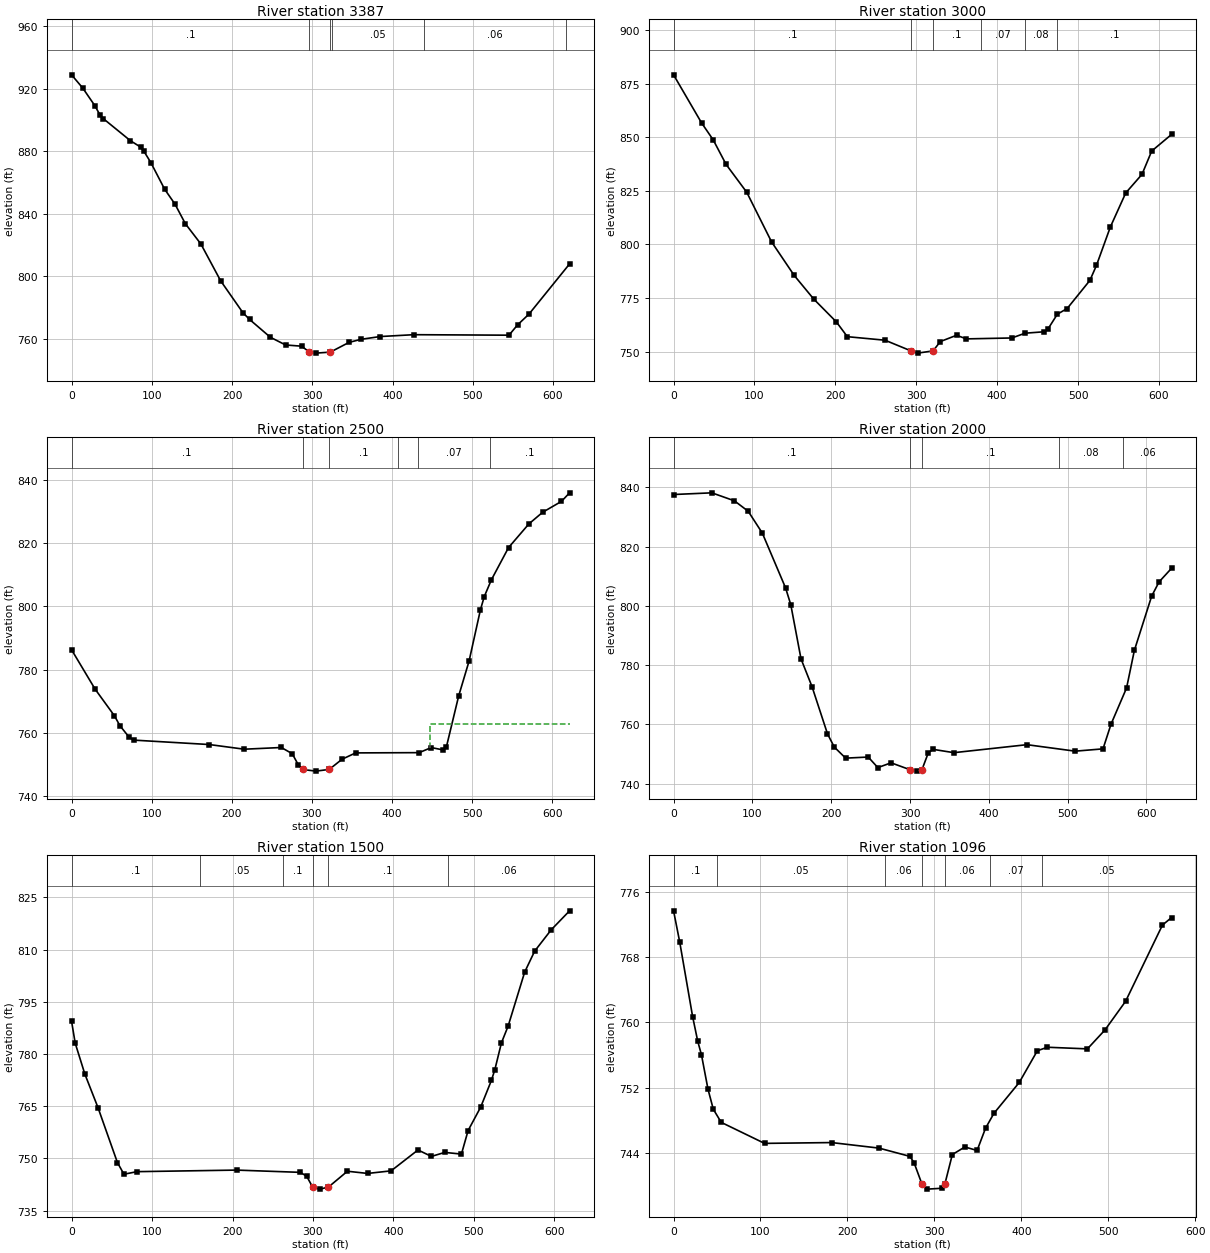
Type RM Length L Ch R = 1 ,3387    ,395.4,387.3,376.7
XS GIS Cut Line= 6
1644330.85801956375407.0272970151644423.43034097375439.301182608
1644507.68378138375472.5996724321644573.84605063375508.784967522
1644654.87180721 375567.394102271644870.78508931375706.152026857
#Sta/Elev= 30
       0  928.87      14  920.36    28.9  909.21    35.2  903.42    39.5  900.85
    73.3  886.73    86.1  882.61    90.3  879.84    98.8  872.72     116  855.67
   128.9  846.12   141.8  833.61   161.2   820.6   185.8  797.06   213.5  776.68
   221.8  772.35   247.8  760.91   266.8  755.98   286.6  755.22   296.5  751.46
   304.6  750.77  322.52  751.42   345.8  757.63   360.6  759.59   384.6  761.38
   426.5  762.57   545.2  762.25   555.8  768.81   570.1  775.74620.7028  807.87
#Mann= 6 ,-1,0
       0      .1       0   296.5    .045       0  322.52      .1       0
  324.04     .05       0  439.14     .06       0  616.81      .1       0
Bank Sta=296.5,322.52
XS Rating Curve= 0 ,0
Exp/Cntr(USF)=0,0
Exp/Cntr=0.3,0.1

Type RM Length L Ch R = 1 ,3000    ,512.8,499.9,488.4
XS GIS Cut Line= 6
1644247.29175392375912.1293794211644342.64655009 375919.56210734
1644431.15129434375921.3862506751644506.14031759 375915.33540976
1644605.66210018375905.2921227511644860.53987126375879.851228759
#Sta/Elev= 30
       0  879.06    34.6  856.65      49  848.72      65  837.24    90.5  824.26
   121.1  801.17   149.1  785.51   173.1  774.55   201.2  763.84   214.8  756.94
   261.4  755.29   293.5  750.31   301.6  749.27  320.79  750.31   329.7  754.66
   349.8   757.6   361.9  755.91   418.2  756.34   434.4  758.56   458.4  759.24
   462.4   760.3   474.4  767.44   486.5  770.07   514.6  783.19   522.7  790.16
   539.9  808.11   558.9  823.97     579  832.65     591  843.51615.5719  851.27
#Mann= 6 ,-1,0
       0      .1       0   293.5    .045       0  320.79      .1       0
  379.43     .07       0   434.4     .08       0   474.4      .1       0
Bank Sta=293.5,320.79
XS Rating Curve= 0 ,0
Exp/Cntr(USF)=0,0
Exp/Cntr=0.3,0.1

Type RM Length L Ch R = 1 ,2500    ,490.4,500,499.3
XS GIS Cut Line= 6
1644334.27550384376591.9452770051644405.06637275376529.630769089
1644468.96421084376469.5583826751644641.58230393376288.718849346
1644717.78457934376241.1323303431644811.83983742376207.306610584
#Sta/Elev= 30
       0  786.25    29.4  773.78    53.6  765.32    60.4   762.2    71.7  758.63
    77.4  757.65   171.8  756.25   215.6  754.77   261.9  755.31   275.5  753.35
   282.9  749.92   288.5  748.35   305.1  747.83   321.7  748.37   337.7  751.59
   354.7   753.6     434  753.68   449.1  755.29   463.3  754.57     468  755.49
   483.3  771.61   496.3  782.66   510.5  798.91   515.3  803.09   524.1  808.36
   545.6   818.6     571  826.09   588.1  829.76   611.7  833.23621.8052  835.93
#Mann= 6 ,-1,0
       0      .1       0   288.5    .045       0   321.7      .1       0
  407.02     .06       0  432.01     .07       0  521.85      .1       0
#XS Ineff= 2 , 0
                          447.14          762.79
Permanent Ineff=
       F       F
Bank Sta=288.5,321.7
XS Rating Curve= 0 ,0
Exp/Cntr(USF)=0,0
Exp/Cntr=0.3,0.1

Type RM Length L Ch R = 1 ,2000    ,517.3,500,495.6
XS GIS Cut Line= 6
1644618.21227193376916.8222519161644764.76840925376801.319202095
   1644827.85785376756.9164037561644982.67610992376675.121619836
1645049.42203942376611.8474681681645109.56037059376530.626830086
#Sta/Elev= 30
       0  837.63    48.6   838.2    77.2   835.5    94.7  831.97   112.6  824.61
   142.1  806.11   148.7  800.47   161.7  782.14   175.7  772.74   195.3  756.82
   203.9  752.36   218.3  748.62     247  748.98   259.2  745.42     276  747.04
   300.4  744.67   308.5  744.23  315.12  744.69   323.2  750.39   329.1  751.59
   355.7  750.46   448.4  753.16   509.6  750.97   544.9  751.75   555.1  760.11
   574.8  772.33   584.7  785.02   606.6   803.3     616  808.12631.8976  812.73
#Mann= 5 ,-1,0
       0      .1       0   300.4    .045       0  315.12      .1       0
  488.87     .08       0  570.84     .06       0
Bank Sta=300.4,315.12
XS Rating Curve= 0 ,0
Exp/Cntr(USF)=0,0
Exp/Cntr=0.3,0.1

Type RM Length L Ch R = 1 ,1500    ,384.7,403.8,413.6
XS GIS Cut Line= 6
1645365.99686559377137.0173495861645379.80261226377037.982442677
1645357.65469067 376953.274278761645285.81625168376713.818392843
1645262.70803018 376629.397958011645239.34915301376538.527732924
#Sta/Elev= 30
       0  789.41     4.5  783.14    16.5  774.25    32.8  764.63      57  748.81
    65.1  745.46    81.3   746.2     205  746.65   284.4     746   292.2  744.87
   299.7  741.72   308.2  741.18  318.95  741.72   342.8  746.32   367.9  745.69
   397.1  746.43   430.5  752.43   447.2  750.58   463.8  751.73   484.5  751.25
   492.8  758.02   508.4  764.74   521.8  772.45     526  775.49   534.2  783.22
   542.5  788.01   563.1  803.55   575.5  809.57   596.2  815.73618.8985  821.15
#Mann= 6 ,-1,0
       0      .1       0  159.99     .05       0  262.55      .1       0
   299.7    .045       0  318.95      .1       0  467.55     .06       0
Bank Sta=299.7,318.95
XS Rating Curve= 0 ,0
Exp/Cntr(USF)=0,0
Exp/Cntr=0.3,0.1

Type RM Length L Ch R = 1 ,1096    ,38,38.1,37.1
XS GIS Cut Line= 3
1645482.70990455  377188.81006841645588.40738852376991.746962708
1645876.83611594376794.683857015
#Sta/Elev= 30
       0  773.67     7.1  769.83    21.9  760.71    27.8  757.68    32.1  756.01
    39.6   751.8    45.7  749.34    54.8  747.73   104.7  745.15   181.9  745.25
   236.4  744.57   271.8  743.56   276.6   742.8  285.86  740.13   291.9  739.54
   309.2  739.65   312.1  740.16   320.7  743.78   335.1  744.71   349.2  744.28
   358.9  747.01   368.6  748.84   397.7  752.62   418.5  756.51   430.1  756.94
   476.1  756.74   496.3  759.06     520  762.57   562.4  771.92572.9406  772.85
#Mann= 7 ,-1,0
       0      .1       0      50     .05       0  243.62     .06       0
  285.86    .045       0   312.1     .06       0  363.62     .07       0
  423.62     .05       0
Bank Sta=285.86,312.1
XS Rating Curve= 0 ,0
Exp/Cntr(USF)=0,0
Exp/Cntr=0.3,0.1

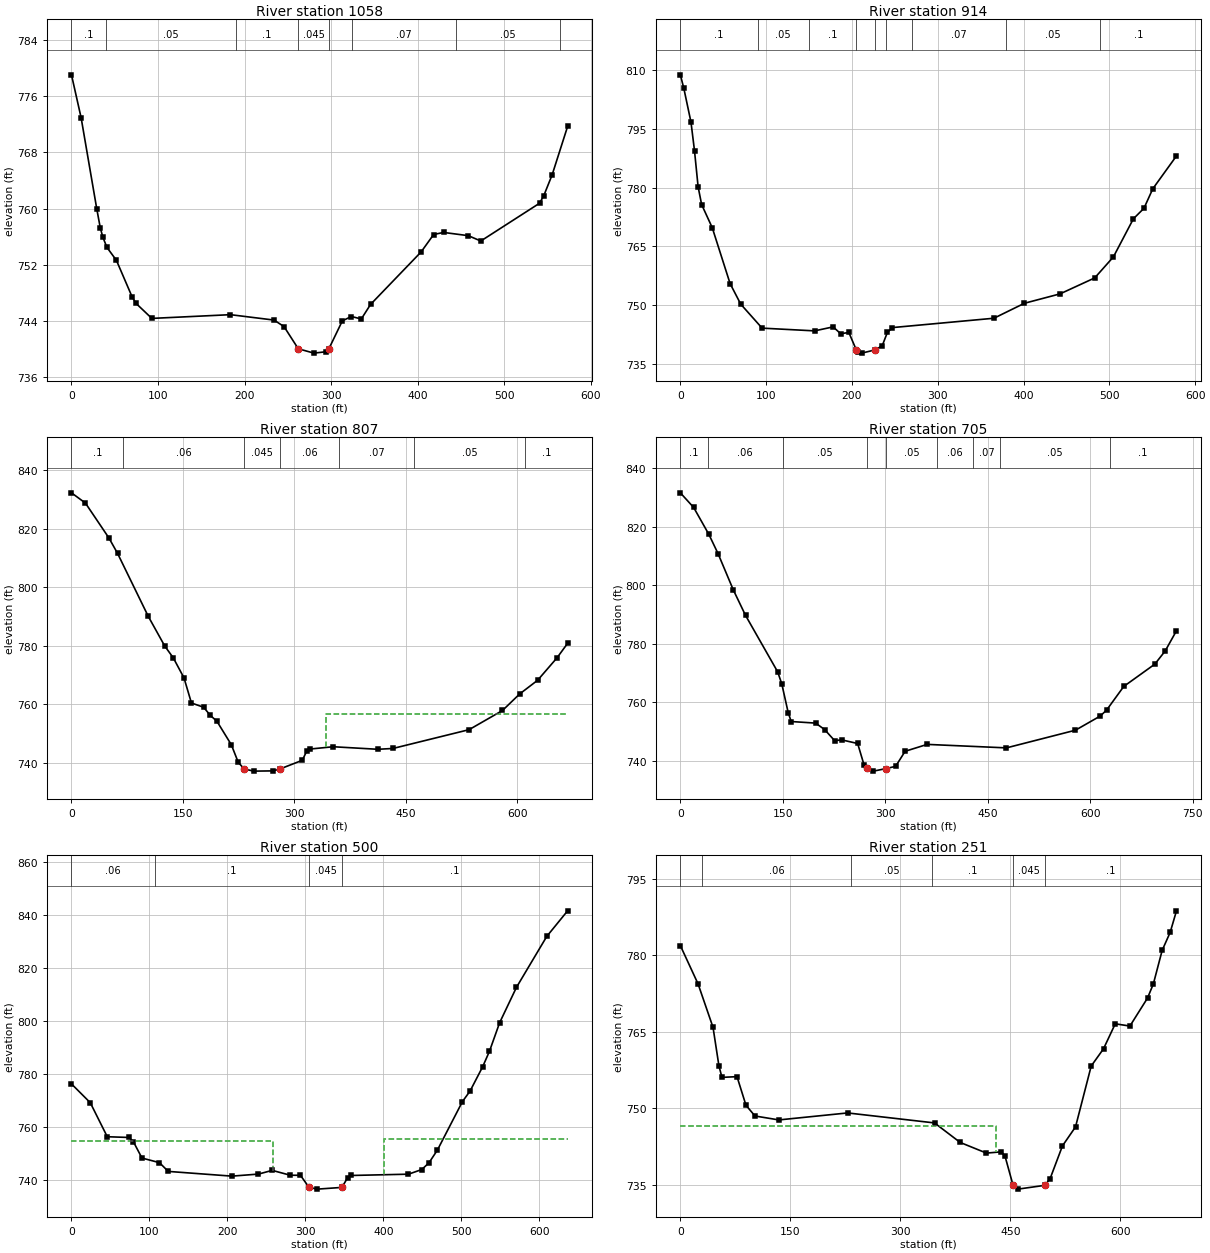
Type RM Length L Ch R = 1 ,1058    ,145.4,144.3,142.7
XS GIS Cut Line= 3
1645516.74807736377210.3078617481645622.44556132377013.244756056
1645910.87428874376816.181650364
#Sta/Elev= 30
       0  779.03    11.1  772.95    29.2  759.97    33.3  757.24    36.3  755.91
      41  754.47    51.9  752.64    70.1  747.42    74.6  746.51    92.8  744.38
   183.6  744.91     234  744.14   245.5  743.21   261.9  740.06     280  739.44
   293.5  739.63   297.3  740.07   312.8  744.03   323.2  744.65   334.7   744.3
   345.4  746.37   403.8  753.84   418.2  756.31   429.7  756.61   458.2  756.15
   472.7  755.39   540.5  760.76   545.4  761.83   555.1  764.81572.9406  771.69
#Mann= 8 ,-1,0
       0      .1       0      40     .05       0     190      .1       0
   261.9    .045       0   297.3     .06       0  323.62     .07       0
  443.62     .05       0  563.62      .1       0
Bank Sta=261.9,297.3
XS Rating Curve= 0 ,0
Exp/Cntr(USF)=0,0
Exp/Cntr=0.3,0.1

Type RM Length L Ch R = 1 ,914     ,123.4,106.8,73.5
XS GIS Cut Line= 4
1645645.73483745377260.4693795611645674.39856191377154.771895599
1645842.79794314377029.3681010671645962.82728933376800.058305352
#Sta/Elev= 30
       0  808.82     4.1  805.33    12.4  796.72    16.5  789.42    20.7  780.21
    24.8  775.66    37.2  769.73      58  755.44    70.4  750.19    95.3  744.06
   156.5  743.36   178.1  744.38   186.9  742.63   196.4  742.95   205.1  738.49
   206.7  737.85   211.4  737.67   227.1   738.5   235.3  739.55   241.3  742.95
   247.2   744.2   365.5  746.59   401.1  750.42   442.6  752.82     483   756.9
   504.8  762.28   528.1  772.02   540.4   774.7   550.7  779.69578.3025  788.09
#Mann= 9 ,-1,0
       0      .1       0      90     .05       0  149.52      .1       0
   205.1    .045       0   227.1      .1       0  239.52     .06       0
  269.52     .07       0  379.48     .05       0  489.48      .1       0
Bank Sta=205.1,227.1
XS Rating Curve= 0 ,0
Exp/Cntr(USF)=0,0
Exp/Cntr=0.3,0.1

Type RM Length L Ch R = 1 ,807     ,107,102.3,122.2
XS GIS Cut Line= 4
1645746.05787307377328.545725164 1645880.4190815377238.971586213
1645805.17680478377109.9848261231646036.27808327376837.679443712
#Sta/Elev= 30
       0  832.33    18.8  828.82    50.5  816.86    62.1  811.59   103.4  790.07
   125.5  779.96   137.1  775.87   151.5  769.03   161.5  760.45     178  758.98
   186.9   756.2   195.7  754.24   215.2  746.18   224.5  740.17  232.56  737.88
   245.4  737.14   270.8  737.22   280.1  737.82   310.8  740.85   316.8  744.03
   321.5   744.7   352.4  745.48   412.4  744.61   432.8  744.89   535.3  751.32
   580.3  757.88   603.4  763.53   627.5   768.2   653.7  775.89667.9632  780.85
#Mann= 7 ,-1,0
       0      .1       0      70     .06       0  232.56    .045       0
   280.1     .06       0  360.81     .07       0  460.81     .05       0
  610.81      .1       0
#XS Ineff= 2 , 0
                          343.06          756.62
Permanent Ineff=
       F       F
Bank Sta=232.56,280.1
XS Rating Curve= 0 ,0
Exp/Cntr(USF)=0,0
Exp/Cntr=0.3,0.1

Type RM Length L Ch R = 1 ,705     ,183.6,204.6,208.8
XS GIS Cut Line= 4
1645766.65992503377350.0435185121645969.09747906377249.720482887
1645872.35740899377083.1125844381646060.46310079376839.470926491
#Sta/Elev= 30
       0  831.55    19.5  826.55    41.8  817.34    55.2  810.79    77.5  798.42
    95.4  789.71   142.5  770.41   148.5  766.31   157.9  756.49   162.3  753.44
   198.1   752.9   211.2   750.7   225.9  746.91   236.3  747.17   259.6  745.94
   268.9  738.66  272.63  737.42   282.8   736.5   301.3  737.38   315.2  738.14
   329.1  743.28   361.4  745.63   477.4  744.44   578.5  750.48   614.6  755.29
     624  757.32   649.2  765.42   694.7  773.04   709.9  777.55 726.397  784.45
#Mann= 9 ,-1,0
       0      .1       0      40     .06       0     150     .05       0
  272.63    .045       0   301.3     .05       0  375.93     .06       0
  428.59     .07       0  468.59     .05       0  628.59      .1       0
Bank Sta=272.63,301.3
XS Rating Curve= 0 ,0
Exp/Cntr(USF)=0,0
Exp/Cntr=0.3,0.1

Type RM Length L Ch R = 1 ,500     ,245.5,248.7,247.2
XS GIS Cut Line= 6
1645923.11418967377505.2971248331645999.94146384377431.065317929
1646068.25038233377361.9850755041646107.85693042 377297.19845967
1646174.66552384377135.4527201651646243.86026734376967.930745512
#Sta/Elev= 30
       0  776.22    24.1  769.12    45.9  756.25    73.7  755.97    79.3   754.4
    90.4  748.19   112.8  746.45   124.1  743.14   205.7  741.35   239.8  742.13
   257.4  743.53   280.6  741.69   293.6  741.67  304.64  737.09   315.3  736.44
  346.79  737.09   354.2  740.82   358.5   741.6   432.1  742.09   449.1  743.84
   458.3  746.35   469.2   751.2   501.3  769.54   511.1  773.53   527.3  782.74
     536  788.59     549  799.36   570.6  812.74   609.5  832.01636.1652  841.66
#Mann= 4 ,-1,0
       0     .06       0  106.83      .1       0  304.64    .045       0
  346.79      .1       0
#XS Ineff= 2 , 0
          259.03  754.49  400.88          755.51
Permanent Ineff=
       F       F
Bank Sta=304.64,346.79
XS Rating Curve= 0 ,0
Exp/Cntr(USF)=0,0
Exp/Cntr=0.3,0.1

Type RM Length L Ch R = 1 ,251     ,84.7,92.7,97.4
XS GIS Cut Line= 5
1645876.45446376377625.353814705 1646085.4130151 377668.45151592
1646178.13837226377544.3823760591646265.63976564377373.297562145
1646269.55773847377257.064367959
#Sta/Elev= 30
       0   781.9    24.2  774.37    44.6  765.84    52.7  758.23    56.8  756.04
    77.3  756.18    89.5  750.57   101.8  748.46   134.4  747.69   228.2  749.06
   346.7   747.1   381.7  743.27   417.5  741.18     438  741.43   442.9  740.55
  453.85  734.85   460.4  734.11   497.4  734.86   504.4  736.19   521.2   742.6
     539  746.32   560.4  758.27   577.2  761.65   593.2  766.55   613.2  766.11
   637.2   771.6   645.2  774.39   657.2  780.97   668.1  784.49676.7094  788.72
#Mann= 6 ,-1,0
       0      .1       0      30     .06       0  233.36     .05       0
  343.36      .1       0  453.85    .045       0   497.4      .1       0
#XS Ineff= 2 , 0
          430.18  746.54
Permanent Ineff=
       F       F
Bank Sta=453.85,497.4
XS Rating Curve= 0 ,0
Exp/Cntr(USF)=0,0
Exp/Cntr=0.3,0.1

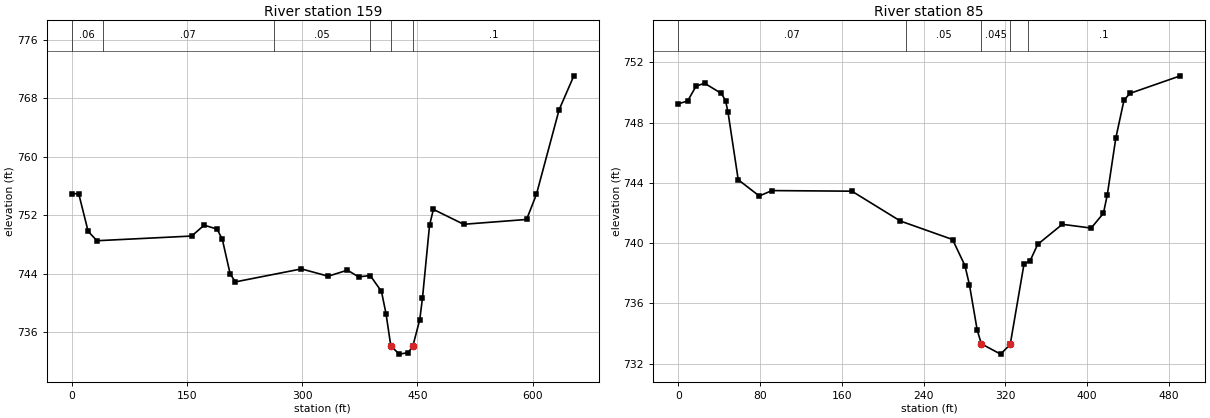
Type RM Length L Ch R = 1 ,159     ,70.9,73.7,72
XS GIS Cut Line= 5
1645935.22405632 377661.921561191646144.18260767377705.019262405
1646236.90796483377580.9501225441646295.67755739377479.082828763
1646282.61764793377311.915987687
#Sta/Elev= 30
       0  754.97     9.1  754.94    21.3   749.8    32.8  748.52   156.1  749.16
   172.3  750.65   189.2  750.11     196  748.69   206.1     744   212.9  742.88
   298.9  744.66   333.8  743.66   358.8  744.49   373.3  743.57   388.5  743.75
   403.1  741.58     409  738.55  415.25  734.14   426.1  732.99     438  733.19
   444.1  734.15   452.9  737.68   456.5  740.66   465.7  750.64   470.7  752.81
   510.1  750.77     592  751.43   604.8  754.86   634.3  766.44653.5281   771.1
#Mann= 6 ,-1,0
       0     .06       0      40     .07       0  263.36     .05       0
  388.25      .1       0  415.25    .045       0   444.1      .1       0
Bank Sta=415.25,444.1
XS Rating Curve= 0 ,0
Exp/Cntr(USF)=0,0
Exp/Cntr=0.3,0.1

Type RM Length L Ch R = 1 ,85      ,,,
XS GIS Cut Line= 5
1646063.21116902377710.243226189 1646182.0563451377740.281017945
1646266.94575658377642.3316970021646315.26742158377563.972240247
1646300.90152118377417.701254306
#Sta/Elev= 30
       0  749.25     9.2  749.44    17.4  750.42    25.7  750.62    42.2  749.94
    46.3  749.46    48.7  748.69    58.7  744.21    79.3  743.13    91.6  743.49
   169.9  743.45   217.3  741.47   268.4  740.24   280.5  738.51   284.9  737.24
   292.5  734.23   296.6  733.31   315.4  732.63   324.8  733.27   338.3  738.61
   344.3  738.83   351.7  739.92   375.8  741.25     404     741     416  741.98
   419.8  743.21   428.1  746.97   436.1  749.48   441.8  749.94491.2339  751.11
#Mann= 5 ,-1,0
       0     .07       0  222.58     .05       0   296.6    .045       0
   324.8     .07       0   342.2      .1       0
Bank Sta=296.6,324.8
XS Rating Curve= 0 ,0
Exp/Cntr(USF)=0,0
Exp/Cntr=0.3,0.1
LCMann Table=0

Chan Stop Cuts=-1
Use User Specified Reach Order=0
Composite Channel Slope=5